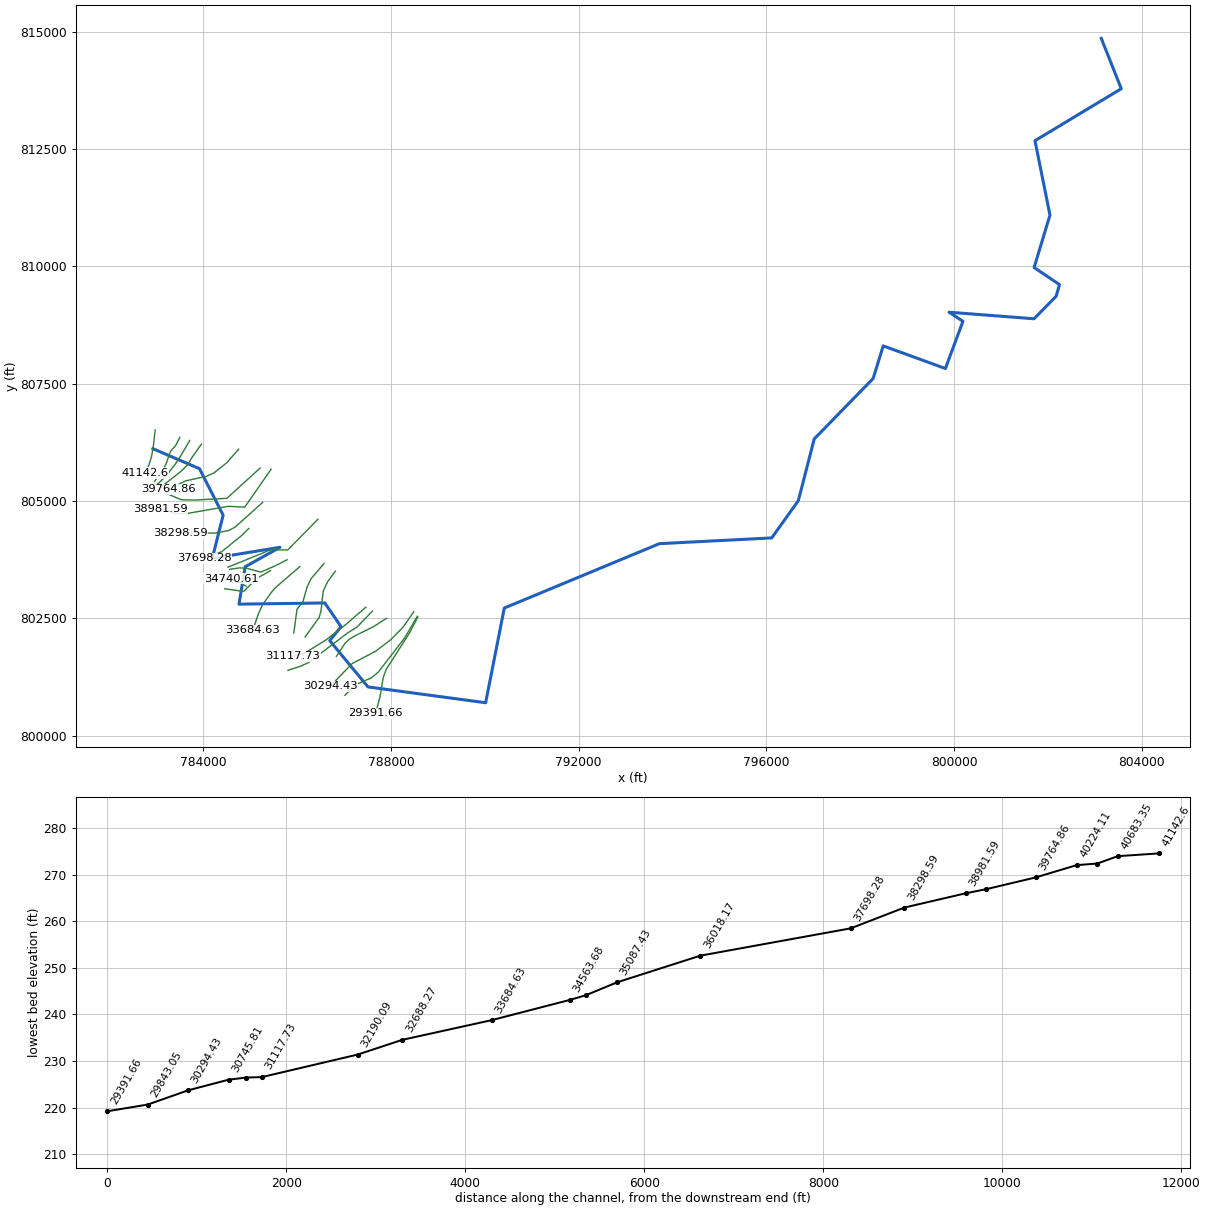
--- 17646_ras.prj (project) ---

Proj Title=17646
Current Plan=p01
Default Exp/Contr=0.3,0.1
English Units
Geom File=g01
Flow File=f01
Plan File=p01
Y Axis Title=Elevation
X Axis Title(PF)=Main Channel Distance
X Axis Title(XS)=Station
BEGIN DESCRIPTION:
RFD model 17646 exported to HEC-RAS
END DESCRIPTION:

--- 17646_ras.p01 (plan) ---

Plan Title=Plan 01
Program Version=4.10
Short Identifier=Plan 01
Geom File=g01
Flow File=f01
Subcritical Flow
Calc Critical at every XS
Secant Critical Depth

--- 17646_ras.f01 (steady flow) ---

Flow Title=Flow 01
Program Version=5.01
Number of Profiles= 6
Profile Names=10yr,25yr,50yr,100yr,100plus,500yr
River Rch & RM=17646,56, 41142.6
 2909.98 5088.82 7298.59 9500.07 13870.1 17521.5
River Rch & RM=17646,56,40683.35
 2921.26 5108.12 7325.89 9535.1113921.2517574.82
River Rch & RM=17646,56,40453.73
 2928.37 5120.28  7343.1 9557.1913953.4917608.41
River Rch & RM=17646,56,40224.11
 2935.34 5132.19 7359.94 9578.7813985.0217641.17
River Rch & RM=17646,56,39764.86
 2944.23 5147.38 7381.41  9606.3 14025.217682.89
River Rch & RM=17646,56,39215.03
 2966.64 5185.69 7435.59 9675.7814126.6317788.26
River Rch & RM=17646,56,38981.59
  2973.8 5197.91 7452.85 9697.8914158.9217821.69
River Rch & RM=17646,56,38298.59
 3079.47 5378.71 7708.6510026.1214638.1318318.73
River Rch & RM=17646,56,37698.28
 3082.76 5384.33  7716.6 10036.314652.9918334.05
River Rch & RM=17646,56,36018.17
 3320.91 5794.67 8299.9710788.1615750.7119477.93
River Rch & RM=17646,56,35087.43
 3330.28 5810.67  8322.610817.1615793.0619521.21
River Rch & RM=17646,56,34740.61
 3333.84 5816.75 8331.2110828.2115809.1919537.72
River Rch & RM=17646,56,34563.68
 3346.99 5839.28 8363.1110869.1615868.9819599.02
River Rch & RM=17646,56,33684.63
 3903.11 6811.42 9758.5212683.3518517.6922375.52
River Rch & RM=17646,56,32688.27
 3922.99 6845.42 9806.6512745.0818607.8122465.66
River Rch & RM=17646,56,32190.09
 3944.84  6882.8 9859.53 12812.918706.8422564.57
River Rch & RM=17646,56,31117.73
 3959.82  6908.4 9895.7312859.32 18774.622632.15
River Rch & RM=17646,56,30942.81
 3960.98 6910.37 9898.5212862.8918779.8322637.35
River Rch & RM=17646,56,30745.81
 3961.97 6912.07 9900.9212865.96 18784.3 22641.8
River Rch & RM=17646,56,30294.43
 3967.59 6921.66 9914.4712883.3318809.6622667.03
River Rch & RM=17646,56,29843.05
 9475.1213518.4216678.6420150.69 32618.529125.59
River Rch & RM=17646,56,29391.66
 9515.4513577.6616752.6920240.8732764.4729256.86
River Rch & RM=17646,56,29115.88
 9566.3813652.4816846.2220354.7932948.8829422.69
River Rch & RM=17646,56, 28488.9
 9636.2713755.1716974.6120511.16   3320229650.33
River Rch & RM=17646,56,28301.51
 9645.3413768.5116991.2820531.4733234.8829679.89
River Rch & RM=17646,56,27543.44
 9712.7113867.5117115.0720682.2533478.95 29899.4
River Rch & RM=17646,56,26042.08
10058.2814375.7117750.6521456.5734732.3731026.87
River Rch & RM=17646,56,25875.62
10069.7314392.5517771.7221482.2534773.9331064.26
River Rch & RM=17646,56,25137.05
10313.8714751.9118221.3422030.1635660.8531862.24
River Rch & RM=17646,56,24006.66
10343.0314794.8618275.0922095.6635766.8831957.64
River Rch & RM=17646,56,23036.57
10369.5314833.8818323.9222155.1735863.2132044.32
River Rch & RM=17646,56,22758.71
10377.2114845.1918338.0722172.4235891.1432069.46
River Rch & RM=17646,56,22256.97
10385.6614857.6418353.6522191.4135921.8832097.12
River Rch & RM=17646,56, 21784.4
10396.4214873.4918373.4822215.5835961.0132132.32
River Rch & RM=17646,56,21263.79
11251.9216134.9419953.0624141.4339078.4334938.37
River Rch & RM=17646,56,21112.58
11255.0416139.5619958.8524148.4839089.8534948.65
River Rch & RM=17646,56,20799.33
12904.65 18579.823019.0127882.8945134.8440394.28
River Rch & RM=17646,56,20397.77
12939.6918631.73 23084.227962.4845263.68 40510.4
River Rch & RM=17646,56,20205.28
12943.71 18637.723091.6927971.6345278.4940523.75
River Rch & RM=17646,56,19173.09
13071.5518827.23 23329.628262.1445748.7540947.62
River Rch & RM=17646,56,18177.99
13156.3918953.0323487.5428455.0146060.9541229.04
River Rch & RM=17646,56, 17182.9
13191.9719005.81 23553.828535.9446191.9441347.12
River Rch & RM=17646,56,16187.81
13214.2219038.8123595.2428586.5446273.8641420.96
River Rch & RM=17646,56,15418.54
13896.9220052.1724868.0330141.2648790.5343690.06
River Rch & RM=17646,56, 15217.3
13898.9620055.2124871.8430145.9248798.0843696.87
River Rch & RM=17646,56,14746.21
13978.7820173.7825020.8230327.9549092.7343962.59
River Rch & RM=17646,56,14314.94
14011.1420221.8625081.2430401.7749212.2344070.36
River Rch & RM=17646,56,13878.09
14036.1420259.0125127.9230458.8149304.5544153.62
River Rch & RM=17646,56,13575.71
 14046.820274.8525147.8230483.1349343.9244189.12
River Rch & RM=17646,56,11002.09
   1488121515.4526707.3932389.1952429.3246972.34
River Rch & RM=17646,56,9010.659
15001.4821694.8126932.9632664.95 52875.7 47375.1
River Rch & RM=17646,56,7766.012
16020.4223213.2928843.64 35001.556657.9450788.68
River Rch & RM=17646,56,6272.435
16043.6223247.8928887.2135054.79 56744.250866.55
River Rch & RM=17646,56,5774.577
16071.0523288.8128938.7135117.7956846.1850958.62
River Rch & RM=17646,56,5027.788
 16089.223315.88 28972.835159.4956913.6851019.55
Boundary for River Rch & Prof#=17646,56,1
Up Type= 0
Dn Type= 2
Boundary for River Rch & Prof#=17646,56,2
Up Type= 0
Dn Type= 2
Boundary for River Rch & Prof#=17646,56,2
Up Type= 0
Dn Type= 2
Boundary for River Rch & Prof#=17646,56,2
Up Type= 0
Dn Type= 2
Boundary for River Rch & Prof#=17646,56,2
Up Type= 0
Dn Type= 2
Boundary for River Rch & Prof#=17646,56,2
Up Type= 0
Dn Type= 2

--- 17646_ras.g01 (geometry) ---

Geom Title=17646
Program Version=4.10

River Reach=17646,56
Reach XY= 30
782929.573281202806115.492683526783921.621975779 805689.14678898
784425.056360336804699.647545978784193.959248721803779.290074933
785635.781595559804014.187536545784894.955628245803600.836060652
 784762.65470335802803.466241375786591.362132731802829.052744288
786938.345384418802323.521581865786696.622069332802025.703582653
787511.794792176801039.617960416790018.996283978  800702.7048468
 790416.35476032 802720.47389441793721.357206912 804092.44868762
796114.733893188804214.724071982796681.531048715805008.054403399
797020.881186097806325.217713629 798275.64311692 807611.16728714
798490.273072481808306.402046285799815.051228702807824.554536903
 800189.17757827808830.364175489799893.921752303809024.220434434
801703.955586794808884.564117934802173.508713964809361.814837335
802247.185668349 809612.53641344801706.154898884809976.522561216
802043.749301762811093.773093323801724.227164331812679.121767809
803562.960442336813786.477291448803136.987580955814860.111351146

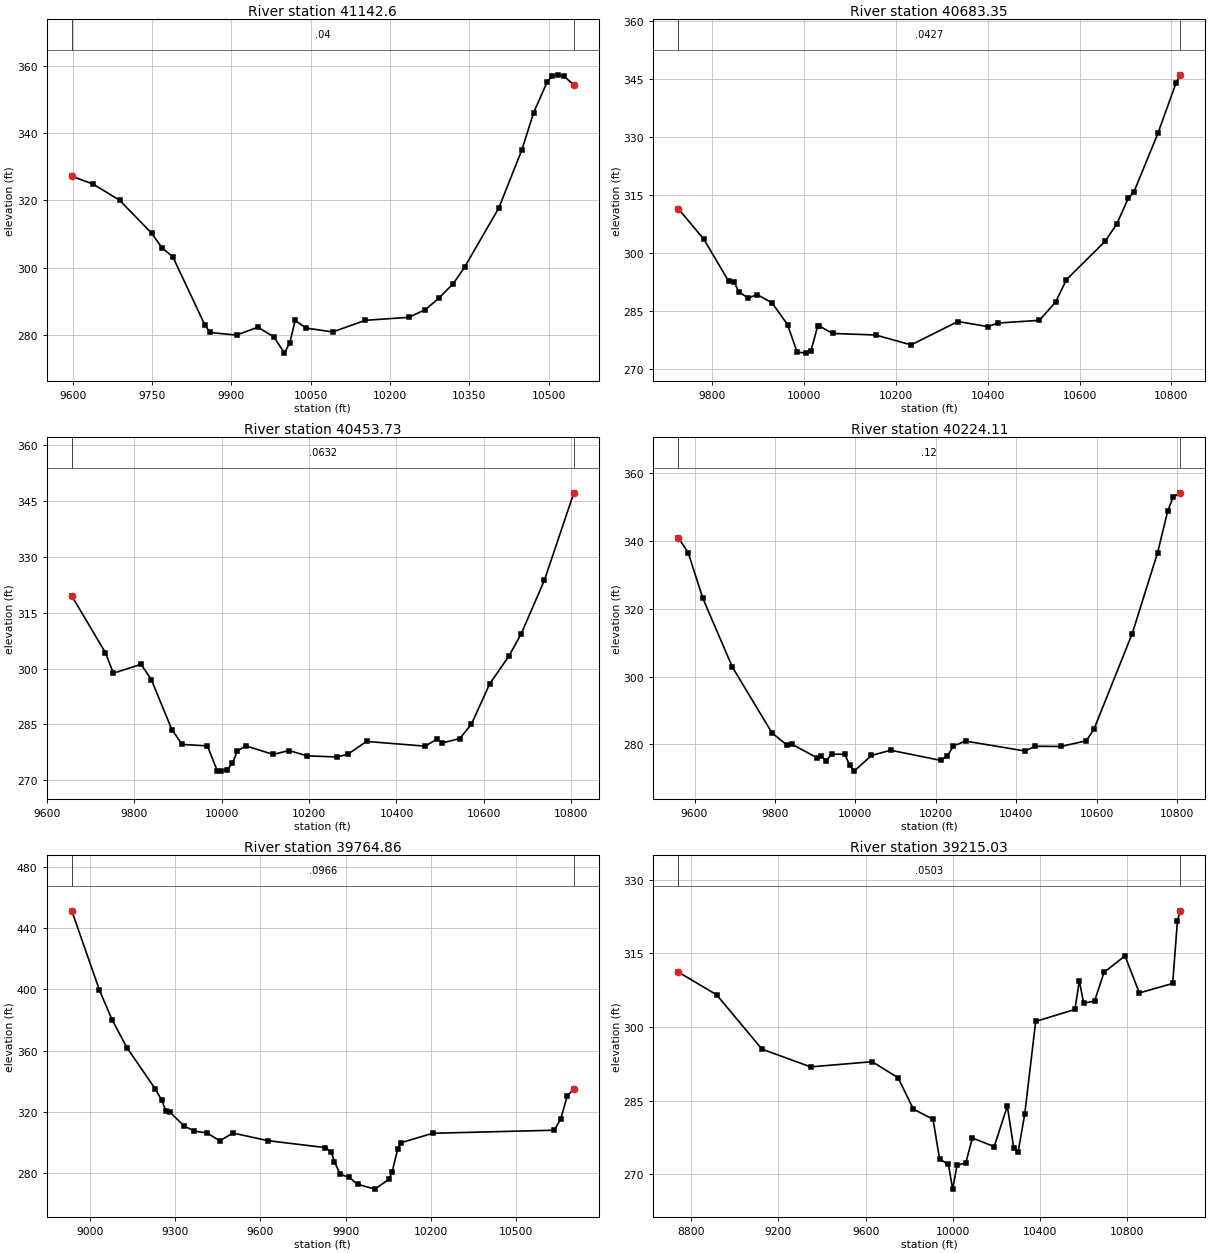
Type RM Length L Ch R = 1 , 41142.6,459.247900,459.247900,459.247900
XS GIS Cut Line= 6
782976.407367182806514.845489726782940.180276263806187.507174702
782904.976600444805976.819805344782884.294879304805893.955436386
782840.732119991  805763.5359477782760.191916335805598.323628617
#Sta/Elev= 30
9597.852327.18899638.009324.88319688.399320.04729748.765310.29859768.872305.8603
9788.979303.24739849.299283.10719859.353280.7432 9909.62279.96329949.912282.3171
9980.177279.464910000.35274.604510010.48277.742510020.62284.318810040.88282.0587
10091.75280.906110153.08284.360910235.68285.241510267.06287.565510291.95290.8735
 10319.7295.2724   10341300.141310405.81 317.74510449.56335.057110471.81346.1247
10496.99355.105110505.82356.944810517.28357.346410528.74357.041210547.84354.2929
#Mann= 3 , 0 , 0
9597.852    0.04       09597.852    0.04       010547.84    0.04       0
#XS Ineff= 2 , 0
       0                               0
Bank Sta=9597.852,10547.84
Exp/Cntr=0.3,0.1

Type RM Length L Ch R = 1 ,40683.35,229.624000,229.624000,229.624000
XS GIS Cut Line= 6
783501.122970892 806355.71042959783413.944361101806184.769098532
783301.895809087806058.771659257783216.098854888805810.174015605
783149.556330864 805672.27290139782963.753752071805418.115312221
#Sta/Elev= 30
9725.907311.41239781.582303.51349835.952292.5963 9847.91292.35369858.052289.8235
9878.599288.25829897.612289.18999930.314287.01349963.917281.41049984.779 274.302
10004.59274.013610014.84274.575510029.75281.031410031.56281.118110062.27279.1095
10155.94278.702610233.12276.141410335.14 282.19810400.26280.876810422.16281.8005
10512.68282.503310547.98287.254810571.51293.041810655.86302.986710680.91307.3951
10706.12314.081910718.72315.808710770.62330.8771 10810.3343.972910819.55346.0608
#Mann= 3 , 0 , 0
9725.907  0.0427       09725.907  0.0427       010819.55  0.0427       0
#XS Ineff= 2 , 0
       0                10439.53       0
Bank Sta=9725.907,10819.55
Exp/Cntr=0.3,0.1

Type RM Length L Ch R = 1 ,40453.73,229.624000,229.624000,229.624000
XS GIS Cut Line= 6
783712.931051772806291.473552604783512.011854625805948.198000869
783417.255497471805805.444828454783260.786428327805600.804888287
783154.108569898805481.759445476783038.554042018805368.248452257
#Sta/Elev= 30
9657.076319.52929733.958304.27589752.321298.74429815.691301.14629839.158296.9925
9886.092283.60379909.559279.6109 9967.43279.20969990.227 272.448    9999272.4288
10012.96272.860110024.36274.501610035.76277.779710054.93279.233510117.85276.9181
   10154277.9709   10195276.545510264.06276.229510288.87276.972110331.51280.4136
10465.77 279.14310491.67280.977210504.96280.001410544.84281.191210571.42285.0292
 10613.2295.8603 10656.7303.245110684.97309.227710738.29323.684710805.83347.2304
#Mann= 3 , 0 , 0
9657.076  0.0632       09657.076  0.0632       010805.83  0.0632       0
#XS Ineff= 2 , 0
       0                10358.49       0
Bank Sta=9657.076,10805.83
Exp/Cntr=0.3,0.1

Type RM Length L Ch R = 1 ,40224.11,459.247900,459.247900,459.247900
XS GIS Cut Line= 6
783964.356216319806215.221658441783768.694819202805939.794000779
783689.951757065805809.106830152783643.019267615805746.689330352
783518.724315666805627.032677505783119.913416154805314.008869499
#Sta/Elev= 30
9559.535340.93749584.133336.57669620.624323.09629694.225302.76529792.608283.3671
9829.502279.8028  9841.8280.04899904.184  276.059915.028276.60159926.948 275.048
9940.934277.08069973.913277.05959985.411273.76679996.908272.085910040.03276.7096
10087.85278.241410211.91 275.26310228.89276.568910243.89279.529510273.89 280.945
 10421.5 278.02410447.11279.420710510.61279.354810574.07281.028510593.26284.4814
 10688.3312.664410751.27 336.49110776.37348.737910789.66352.861410807.85354.1825
#Mann= 3 , 0 , 0
9559.535    0.12       09559.535    0.12       010807.85    0.12       0
#XS Ineff= 2 , 0
       0                 10254.8       0
Bank Sta=9559.535,10807.85
Exp/Cntr=0.3,0.1

Type RM Length L Ch R = 1 ,39764.86,549.831800,549.831800,549.831800
XS GIS Cut Line= 6
784756.384494055806104.668093457784497.532221279805812.512102843
784229.529090954805599.682464512784068.242474214805526.533724208
783627.741785546805431.034223413783264.666546242805252.919559172
#Sta/Elev= 30
8936.103451.33839033.613399.4774  9078.2380.06919130.788361.79069230.247334.8981
9253.259327.45149267.251320.44249281.244319.84969330.159310.96699367.129307.3435
9412.048306.19669457.145301.03999503.971306.08379627.187301.10339829.428296.5674
 9850.49293.41639860.813287.28519881.459279.11269912.132277.17119942.605272.6447
10003.18269.444710053.68275.983910063.78280.570310083.98295.686510094.08 299.719
10206.96 305.948 10635.1307.958210657.88315.485310680.66330.444910703.82334.8281
#Mann= 3 , 0 , 0
8936.103  0.0966       08936.103  0.0966       010703.82  0.0966       0
#XS Ineff= 2 , 0
       0                               0
Bank Sta=8936.103,10703.82
Exp/Cntr=0.3,0.1

Type RM Length L Ch R = 1 ,39215.03,233.436500,233.436500,233.436500
XS GIS Cut Line= 5
785213.261338264805703.390206903784503.089957803805057.565335229
783812.805194527805021.427532509783528.329804718805028.322530657
783192.893551707805175.585346177
#Sta/Elev= 30
8740.999311.20758916.966306.57289125.053295.48079348.004291.86729630.408292.9228
9749.068289.64149819.163283.25039909.287281.18189939.328273.04429979.383272.0134
 9999.41266.932310019.44271.823610059.49272.262210089.53277.368310189.67275.5971
10249.75283.854610279.79275.228910299.82274.593610329.86282.286410379.93301.1468
   10560303.5802   10580309.428810600.01304.855610650.02305.307710693.31311.1512
10789.55314.508810855.08306.951111007.97308.883111029.82321.672911043.04323.6978
#Mann= 3 , 0 , 0
8740.999  0.0503       08740.999  0.0503       011043.04  0.0503       0
#XS Ineff= 2 , 0
       09789.818        10194.41       0
Bank Sta=8740.999,11043.04
Exp/Cntr=0.3,0.1

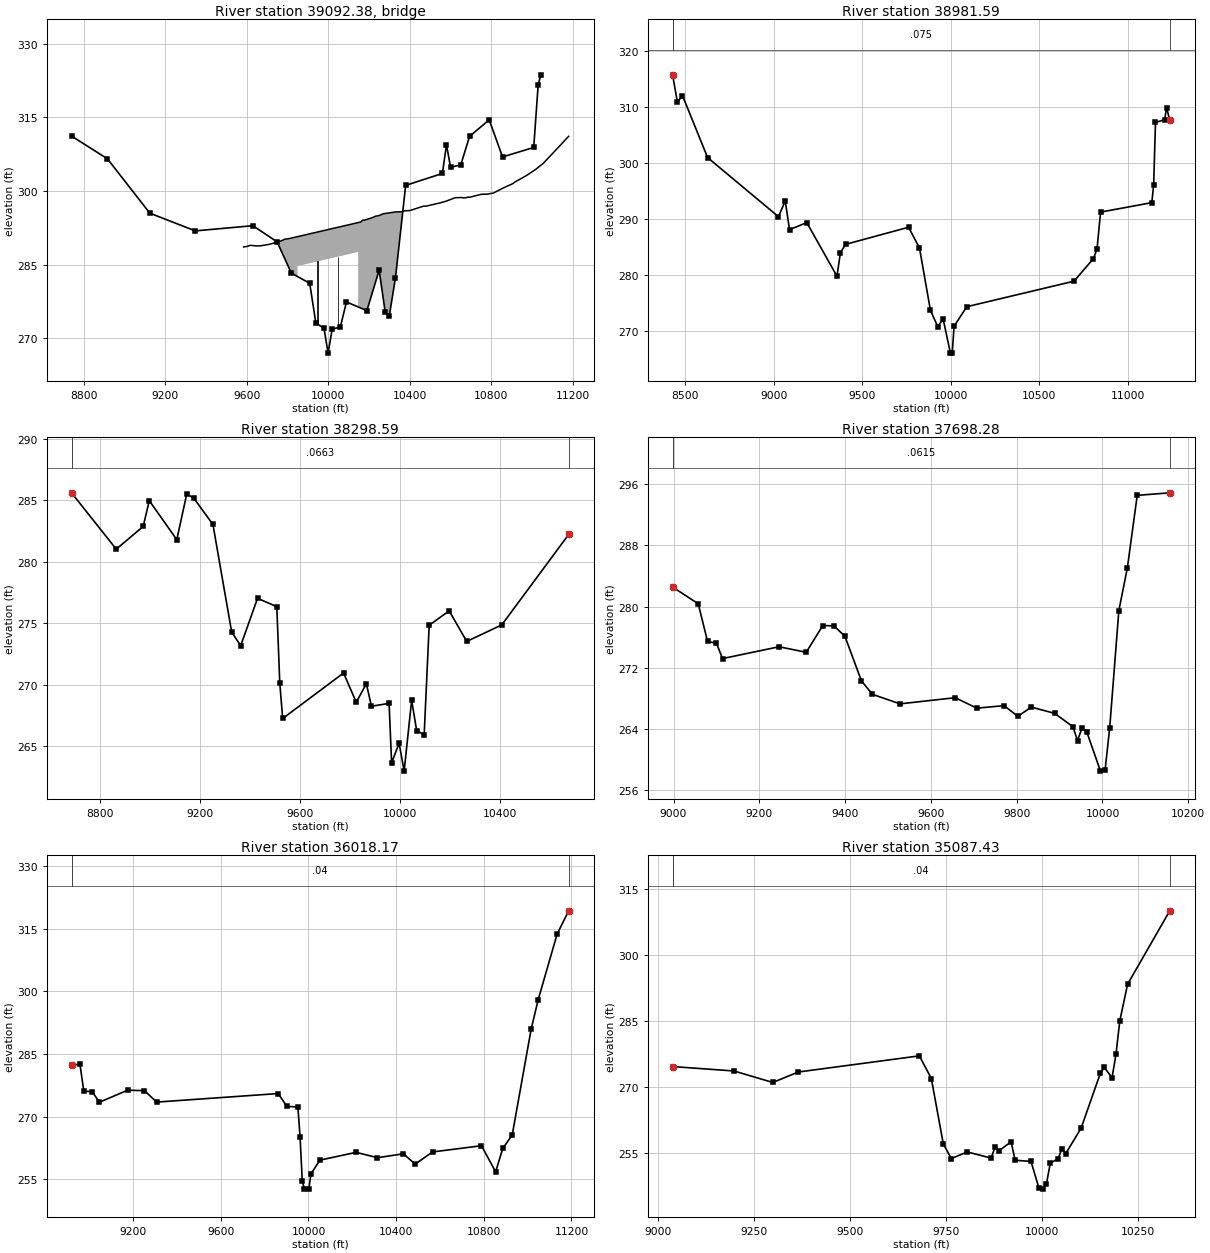
Type RM Length L Ch R = 3 ,39092.38,,,
BEGIN DESCRIPTION:
END DESCRIPTION:
Bridge Culvert--1,0,-1,-1, 0
Deck Dist Width WeirC Skew NumUp NumDn MinLoCord MaxHiCord MaxSubmerge Is_Ogee
76.218250,81.000000,2.6,0, 46, 46, , , 0.95, 0, 0,0,,
 9584.90 9603.35 9619.66 9644.73 9665.43 9706.81 9730.61 9747.84 9768.11 9788.37
 9805.68 9849.61 9849.6110146.6110146.6110159.5910169.3710179.6810220.0610230.08
10250.1410270.2010330.3710360.4610370.4910400.5810467.8910480.8410551.2310581.39
10621.6110652.9710663.4510673.9310684.0610694.8910751.0510778.7110810.1410857.04
10905.6010916.3410970.0011017.6211055.8711179.45
  288.59  288.71  288.93  288.80  288.81  289.09  289.34  289.63  289.81  290.19
  290.27  290.69  290.69  293.56  293.56  293.69  294.05  294.08  294.62  294.84
  295.01  295.36  295.73  295.78  295.93  296.01  296.92  296.92  297.60  297.97
  298.62  298.68  298.59  298.61  298.75  298.74  299.33  299.36  299.58  300.59
  301.51  301.85  303.10  304.41  305.68  311.16
 -711.41 -711.29 -711.07 -711.20 -711.19 -710.91 -710.66 -710.37 -710.19 -709.81
 -709.73 -709.31  284.69  287.56 -706.44 -706.31 -705.95 -705.92 -705.38 -705.16
 -704.99 -704.64 -704.27 -704.22 -704.07 -703.99 -703.08 -703.08 -702.40 -702.03
 -701.38 -701.32 -701.41 -701.39 -701.25 -701.26 -700.67 -700.64 -700.42 -699.41
 -698.49 -698.15 -696.90 -695.59 -694.32 -688.84
 9584.90 9603.35 9619.66 9644.73 9665.43 9706.81 9730.61 9747.84 9768.11 9788.37
 9805.68 9838.55 9838.5510135.5510135.5510159.5910169.3710179.6810220.0610230.08
10250.1410270.2010330.3710360.4610370.4910400.5810467.8910480.8410551.2310581.39
10621.6110652.9710663.4510673.9310684.0610694.8910751.0510778.7110810.1410857.04
10905.6010916.3410970.0011017.6211055.8711179.45
  288.59  288.71  288.93  288.80  288.81  289.09  289.34  289.63  289.81  290.19
  290.27  290.58  290.58  293.45  293.45  293.69  294.05  294.08  294.62  294.84
  295.01  295.36  295.73  295.78  295.93  296.01  296.92  296.92  297.60  297.97
  298.62  298.68  298.59  298.61  298.75  298.74  299.33  299.36  299.58  300.59
  301.51  301.85  303.10  304.41  305.68  311.16
 -711.41 -711.29 -711.07 -711.20 -711.19 -710.91 -710.66 -710.37 -710.19 -709.81
 -709.73 -709.42  284.58  287.45 -706.55 -706.31 -705.95 -705.92 -705.38 -705.16
 -704.99 -704.64 -704.27 -704.22 -704.07 -703.99 -703.08 -703.08 -702.40 -702.03
 -701.38 -701.32 -701.41 -701.39 -701.25 -701.26 -700.67 -700.64 -700.42 -699.41
 -698.49 -698.15 -696.90 -695.59 -694.32 -688.84
Pier Skew, UpSta & Num, DnSta & Num=  ,9947.94, 2 ,9936.89, 2 , 0 , 0 , 0 ,,
    4.00    4.00
 -708.36  291.64
    4.00    4.00
 -708.47  291.53
Pier Skew, UpSta & Num, DnSta & Num=  ,10048.28, 2 ,10037.22, 2 , 0 , 0 , 0 ,,
    4.00    4.00
 -707.39  292.61
    4.00    4.00
 -707.50  292.50
BR Coef=-1 , 0 , 0 ,, 0 ,,,0.8,0,1,0,
WSPro=,,,, 1 ,,,, 0 ,,,, 0 ,,,,-1 ,-1 ,-1 , 0 , 0 , 0 , 0 , 0
BC Design=,, 0 ,, 0 ,,,,,,

Type RM Length L Ch R = 1 ,38981.59,683.003800,683.003800,683.003800
XS GIS Cut Line= 6
 785446.87988323805677.432590812  784885.6833179 804871.14245595
784537.206563175804888.200758651783659.922425359804735.894484729
783435.167476684804734.771839052783087.441657215804831.985509008
#Sta/Elev= 30
8428.619315.70628455.951310.82518484.425312.01368626.524 300.9359027.076290.3822
 9065.14293.20779089.508 288.0749186.978289.32959357.551279.76389377.173283.9757
9406.287285.4452 9762.15288.50019823.871 284.8029885.592273.69379926.739270.7829
9957.599272.12449998.746266.030910009.03 266.12610019.32270.827710091.33274.3168
10697.22278.873610807.23282.912810827.23284.632810847.23291.202111136.82292.8899
 11147.2296.053911157.59307.2262 11209.5307.679611219.89309.871911238.12307.6305
#Mann= 3 , 0 , 0
8428.619   0.075       08428.619   0.075       011238.12   0.075       0
#XS Ineff= 2 , 0
       09800.141        10174.53       0
Bank Sta=8428.619,11238.12
Exp/Cntr=0.3,0.1

Type RM Length L Ch R = 1 ,38298.59,600.306700,600.306700,600.306700
XS GIS Cut Line= 6
785267.942067593804972.735144824784682.173988968804446.442649633
784540.797622383804371.681652337784248.607190907804317.011051804
783747.116605699804327.857059047783508.178701848 804311.50481078
#Sta/Elev= 30
8688.171285.5938 8866.89281.01598974.437282.85718998.996284.9567 9108.87281.7867
9148.622285.49249176.087285.1805 9253.36 283.0219328.173274.27929364.294273.1664
9431.511277.02089508.574276.33819520.566270.10529532.105267.25039775.494 270.949
9826.094268.56669866.575270.07389886.815268.24699957.393268.47929967.403263.6518
9997.463265.236810017.51262.971910047.57268.728810067.58 266.26710097.59265.9339
 10117.6274.833510197.62276.000110267.65 273.51410407.68274.857910675.13  282.21
#Mann= 3 , 0 , 0
8688.171  0.0663       08688.171  0.0663       010675.13  0.0663       0
#XS Ineff= 2 , 0
       09706.936                       0
Bank Sta=8688.171,10675.13
Exp/Cntr=0.3,0.1

Type RM Length L Ch R = 1 ,37698.28,1680.104600,1680.104600,1680.104600
XS GIS Cut Line= 4
784972.803178698804417.179589286784824.520542204804269.467469469
784394.153142244803921.264085472784024.184378505803779.705084607
#Sta/Elev= 30
8997.773282.55559057.539280.37559079.362275.44559100.047 275.2199114.217273.2117
9245.972274.75619309.362274.03339347.951277.53299373.678  277.489399.404276.1457
9437.994270.2978 9463.72  268.549528.036267.29579656.668268.09899707.028266.7313
9770.463267.06399802.584265.67159834.158266.8668 9888.24266.06179931.068 264.314
9941.775262.49889952.482264.17339963.189263.6633 9995.31258.506410006.02258.6313
10016.72264.108510038.14279.478510058.02285.075510080.97 294.53910156.79294.8682
#Mann= 3 , 0 , 0
8997.773  0.0615       08997.773  0.0615       010156.79  0.0615       0
#XS Ineff= 2 , 0
       0 9585.71                       0
Bank Sta=8997.773,10156.79
Exp/Cntr=0.3,0.1

Type RM Length L Ch R = 1 ,36018.17,930.748600,930.748600,930.748600
XS GIS Cut Line= 6
786444.157345355804612.492089286785804.605197191803960.359816983
785616.698874325803958.363602385785522.342432708803979.043560579
785452.941428185803967.961243182784526.250310272803590.928294271
#Sta/Elev= 30
8918.413 282.289 8956.92282.54018974.337276.11459012.945 275.9549045.747273.4285
9174.284 276.3199251.054276.2042 9307.08273.47139861.478275.51639901.554272.4306
9951.569 272.3199961.571265.14649971.573254.58869981.574252.640410001.58252.7676
10011.59256.314310052.29259.581710217.28261.442310314.44 260.164 10433.2261.0937
10486.85258.630710566.46261.540210789.46 263.03110854.24 256.78210886.63262.3816
10929.81265.595611016.18290.908411048.57298.019411134.93313.709311187.56319.2515
#Mann= 3 , 0 , 0
8918.413    0.04       08918.413    0.04       011187.56    0.04       0
#XS Ineff= 2 , 0
       0                10213.26       0
Bank Sta=8918.413,11187.56
Exp/Cntr=0.3,0.1

Type RM Length L Ch R = 1 ,35087.43,346.820000,346.820000,346.820000
XS GIS Cut Line= 6
 785787.10100469803750.122398794785529.997720242803617.966504917
785227.240581542803485.810611039784913.558244367803572.213937557
784764.327576549803575.421784716784566.461112171803545.881471887
#Sta/Elev= 30
9038.549274.73289198.323273.73289299.517271.11969365.815273.49949681.071277.1646
9712.229272.00979743.386257.17429764.158253.85529805.701255.35139868.016253.9568
9878.402256.56289888.788255.64499919.945257.67159930.331253.46949971.709 253.204
9991.953247.254310001.97246.910810011.98248.123610021.99252.869810042.03253.7514
10052.05256.050310062.08254.979510102.17260.756210152.39273.2442 10162.5274.5282
10182.72272.222910192.84277.485910202.95285.154410223.17293.426410332.91310.0887
#Mann= 3 , 0 , 0
9038.549    0.04       09038.549    0.04       010332.91    0.04       0
#XS Ineff= 2 , 0
       09857.301                       0
Bank Sta=9038.549,10332.91
Exp/Cntr=0.3,0.1

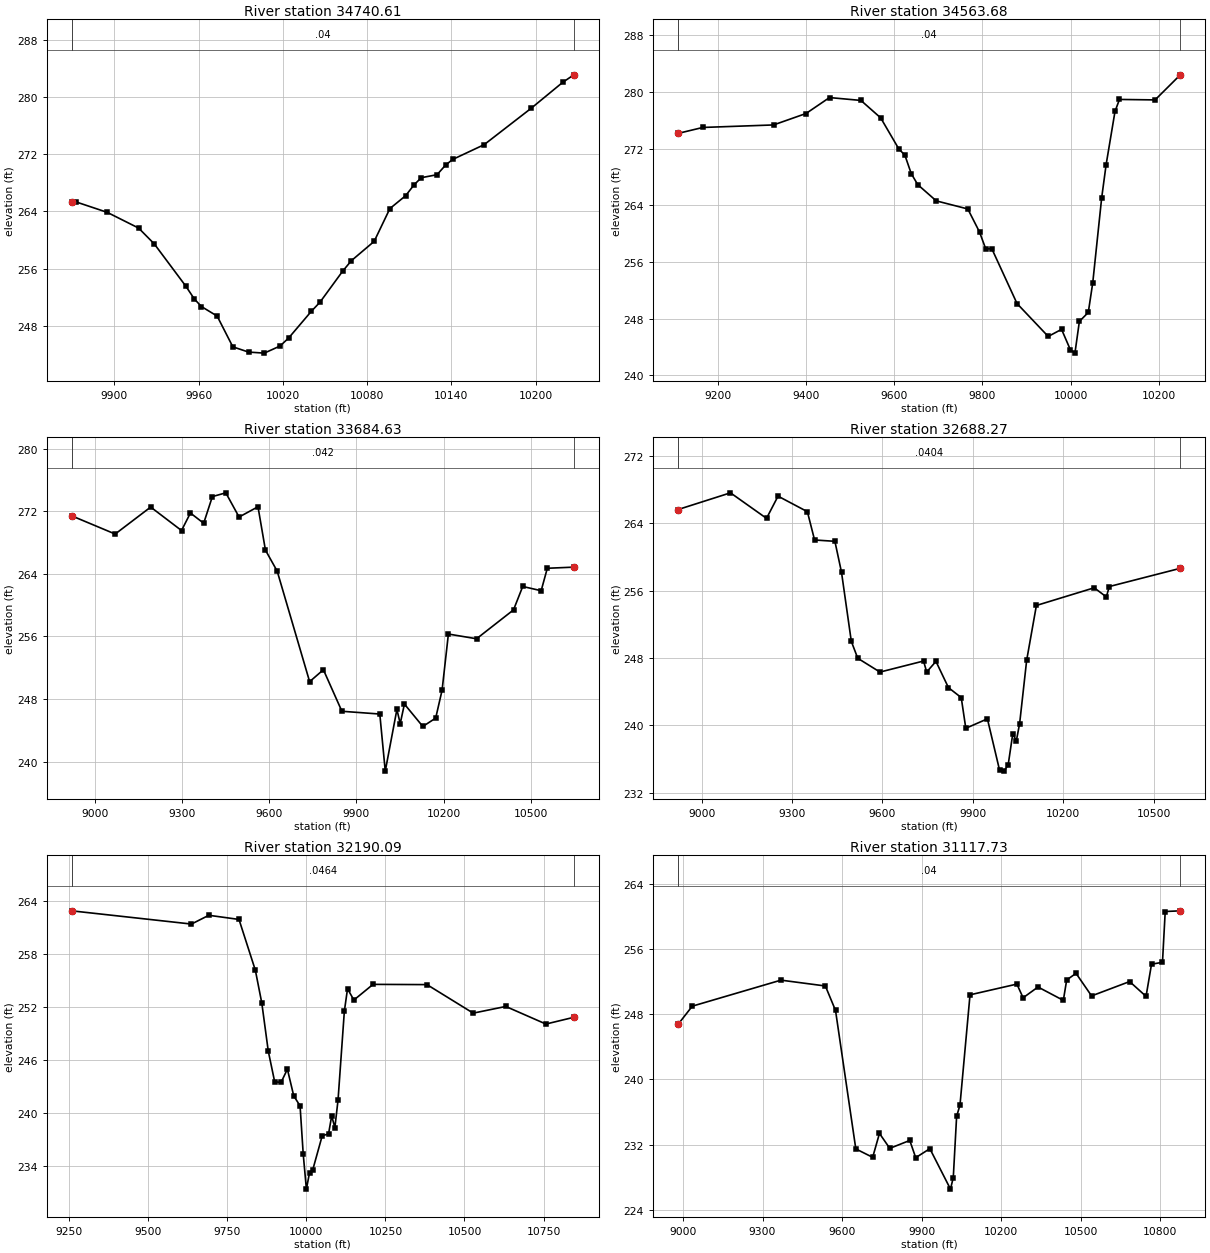
Type RM Length L Ch R = 1 ,34740.61,176.929600,176.929600,176.929600
XS GIS Cut Line= 2
784917.637901217803185.935217276784597.877934873803345.815200463
#Sta/Elev= 30
9869.689265.27249872.638265.35339894.999263.88189917.359261.6767 9928.54259.4508
  9950.9253.5512 9957.04251.73659962.081250.67759973.261249.34319984.441245.0299
9995.622244.2973 10006.8244.149310017.98 245.13910024.12246.258110040.34250.0146
10046.48251.2894 10062.7255.657910068.84257.109210085.06259.815910096.24264.4107
10107.43266.210810113.57 267.76510118.61268.737910129.79269.155710135.93270.5137
10140.97271.300710163.33273.365610196.87 278.47510219.23 282.09610227.19283.1554
#Mann= 3 , 0 , 0
9869.689    0.04       09869.689    0.04       010227.19    0.04       0
#XS Ineff= 2 , 0
       0                               0
Bank Sta=9869.689,10227.19
Exp/Cntr=0.3,0.1

Type RM Length L Ch R = 1 ,34563.68,879.044600,879.044600,879.044600
XS GIS Cut Line= 4
785433.884342879803517.047458678785138.335707486803351.251882732
          784865803073.051858544784458.333562642803132.593949229
#Sta/Elev= 30
9109.104274.17029165.155275.00819325.679275.36299399.441276.9781 9452.74279.2283
9524.083 278.8229568.897276.36219609.694 272.0159623.962271.07239638.231268.4965
9653.012 266.9369695.069264.64359766.648263.50189793.202260.25319807.221257.8853
 9821.24257.87839878.417250.14489949.163245.50659979.483246.50949999.696243.5891
 10009.8243.151110019.91 247.62710040.12248.899210050.23253.069410070.44265.0364
10080.55269.742610100.76277.268310110.87 278.96310191.72278.896510248.99282.4374
#Mann= 3 , 0 , 0
9109.104    0.04       09109.104    0.04       010248.99    0.04       0
#XS Ineff= 2 , 0
       0                               0
Bank Sta=9109.104,10248.99
Exp/Cntr=0.3,0.1

Type RM Length L Ch R = 1 ,33684.63,996.358700,996.358700,996.358700
XS GIS Cut Line= 6
786060.042762011803603.377505928785536.298280711803152.376451577
785456.880491355803058.868332822785264.374562705802791.103414263
785179.109801402802602.027908389785056.286528433802248.621034193
#Sta/Elev= 30
8919.989271.42079069.767269.09049191.913272.54049298.007269.53959328.589271.7781
9374.263270.47149404.101273.87739450.387  274.369496.061271.26519561.112  272.58
9586.723267.03539627.201 264.3459738.796250.21459786.154251.74179849.805246.4297
9980.209246.0771    9999238.777110039.05246.658510050.51 244.85210064.87247.3516
10128.26244.488110172.49245.557810194.52249.128210216.21256.305110313.09255.7004
10440.27259.393810471.98262.387610535.39261.843910556.53264.714710647.83264.8589
#Mann= 3 , 0 , 0
8919.989   0.042       08919.989   0.042       010647.83   0.042       0
#XS Ineff= 2 , 0
       09860.431                       0
Bank Sta=8919.989,10647.83
Exp/Cntr=0.3,0.1

Type RM Length L Ch R = 1 ,32688.27,498.179300,498.179300,498.179300
XS GIS Cut Line= 6
786576.508625639803668.886108821786297.619467797803345.961419508
 786210.72674889803158.935065525786124.852383296802850.542523252
785999.722198776802695.725643668785930.842962671802191.883465093
#Sta/Elev= 30
8922.195265.61549095.866267.5977  9215.5264.56669253.727267.20339351.033265.3593
9374.926261.99949442.327261.84159464.262258.16929496.789249.96689518.132247.9595
9591.902246.31839736.501247.63019746.788246.3281 9777.65247.58479819.077244.4721
9861.483243.29069876.667239.64299948.289240.76739988.609234.681410003.59234.5587
10017.22235.306710032.47238.990810044.36238.165210055.18240.187810078.57247.7162
10110.85254.225310302.76256.324210342.84255.242310352.86256.473410588.32258.6365
#Mann= 3 , 0 , 0
8922.195  0.0404       08922.195  0.0404       010588.32  0.0404       0
#XS Ineff= 2 , 0
       09749.376                       0
Bank Sta=8922.195,10588.32
Exp/Cntr=0.3,0.1

Type RM Length L Ch R = 1 ,32190.09,1072.363000,1072.363000,1072.363000
XS GIS Cut Line= 6
786817.723536042803507.427741373786647.792978851803274.898390936
786558.013160336803079.900507457786510.235039286802658.173487324
786471.559409788802520.212836139786171.457997252802103.093265712
#Sta/Elev= 30
9257.601262.88069636.502261.38369691.423 262.3769786.837261.90739838.654256.1489
9859.007252.44289879.359247.0254 9899.65243.54719919.774243.46399939.898244.9637
9959.964241.94689979.992240.81679990.007235.337410000.02231.395910010.03233.2756
10020.03233.569710050.03237.433610070.03237.644710080.03239.683310090.03238.3519
10100.03241.455210120.05251.524710130.09  254.0610150.19252.787510210.82 254.561
10381.39254.532410527.56251.305910630.65252.061310757.51250.071910845.84250.8353
#Mann= 3 , 0 , 0
9257.601  0.0464       09257.601  0.0464       010845.84  0.0464       0
#XS Ineff= 2 , 0
       0                               0
Bank Sta=9257.601,10845.84
Exp/Cntr=0.3,0.1

Type RM Length L Ch R = 1 ,31117.73,174.922100,174.922100,174.922100
XS GIS Cut Line= 6
787465.424706489802738.360144824787043.903267652802374.602500141
786824.509592354802201.371790767  786607.3983289802034.215331301
786159.869150907801759.193478152785909.869150907801694.957367063
#Sta/Elev= 30
8981.771246.75249035.167248.9742 9369.57252.16439537.099251.44769575.375248.4446
9651.823231.48289715.411230.44899741.014233.37959779.959231.5491 9855.33232.5188
9877.708230.40719931.053231.510410008.85226.5521 10019.4227.974410032.02235.4804
10044.64236.8479 10082.5250.364210259.23251.6796 10282.7250.001110338.89251.3233
10434.39249.685110447.03252.183510482.24252.997510540.93250.231710684.35251.9906
 10746.3250.176410766.95254.120610808.25254.347510818.57260.575610875.49260.6588
#Mann= 3 , 0 , 0
8981.771    0.04       08981.771    0.04       010875.49    0.04       0
#XS Ineff= 2 , 0
       09837.907        10085.67       0
Bank Sta=8981.771,10875.49
Exp/Cntr=0.3,0.1

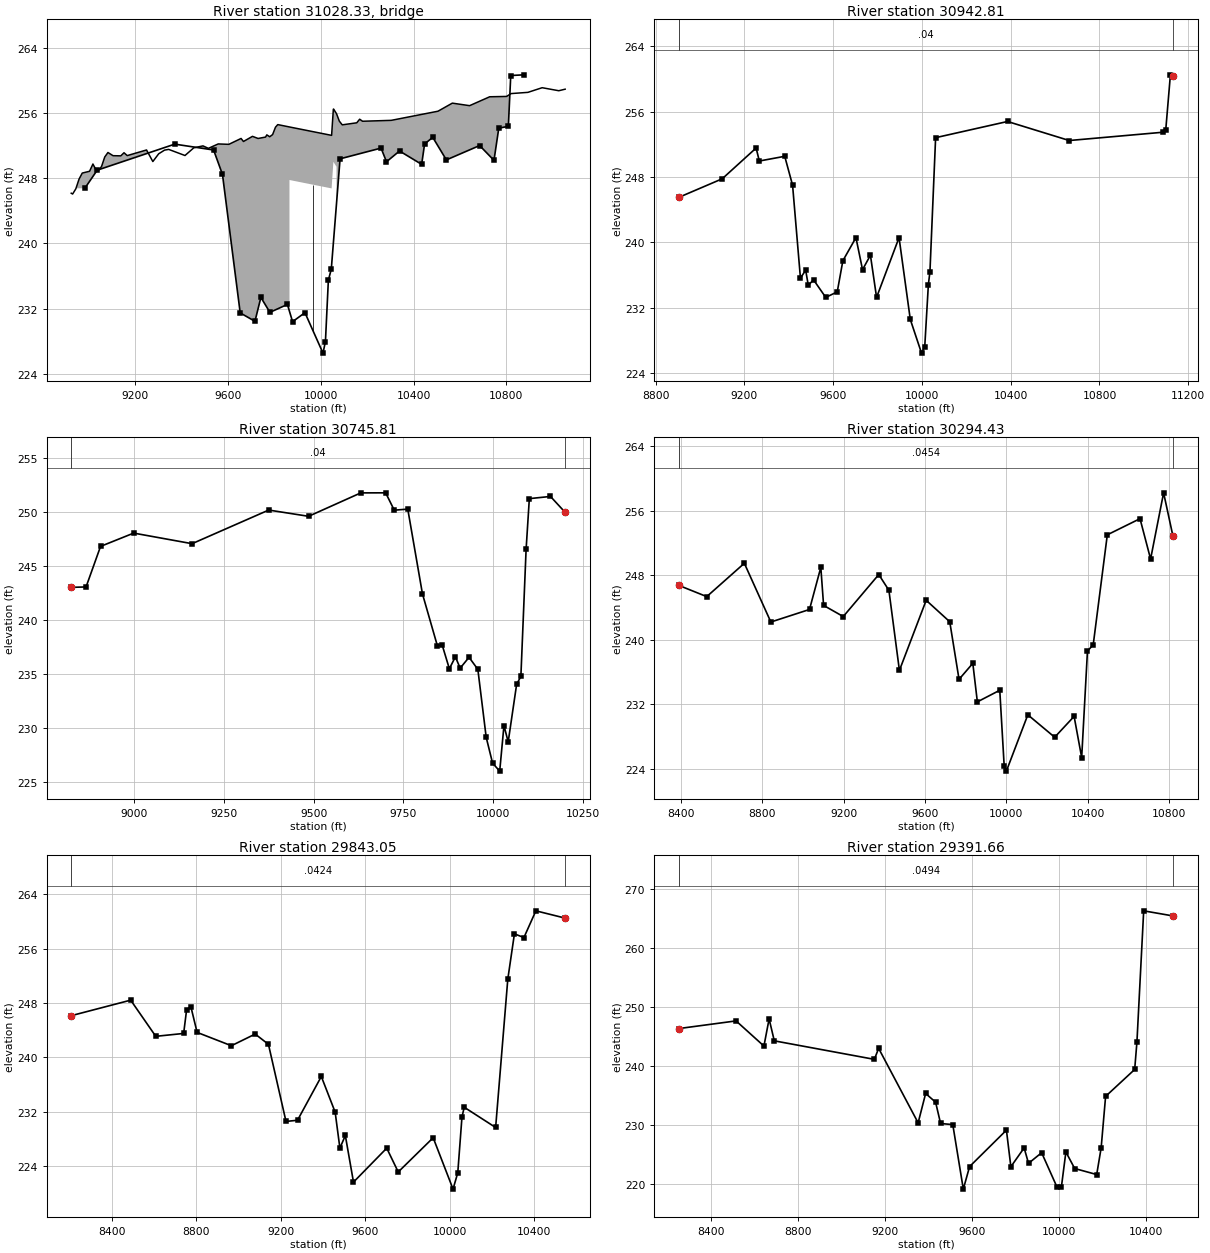
Type RM Length L Ch R = 3 ,31028.33,,,
BEGIN DESCRIPTION:
END DESCRIPTION:
Bridge Culvert--1,0,-1,-1, 0
Deck Dist Width WeirC Skew NumUp NumDn MinLoCord MaxHiCord MaxSubmerge Is_Ogee
54.961050,65.000000,2.6,0, 60, 60, , , 0.95, 0, 0,0,,
 8923.15 8929.13 8942.98 8956.83 8970.68 9002.22 9016.67 9031.12 9039.93 9053.78
 9067.63 9081.49 9103.39 9136.89 9150.74 9164.59 9247.92 9275.05 9300.26 9325.47
 9343.42 9413.70 9451.51 9491.27 9514.53 9556.98 9602.76 9655.55 9665.78 9704.84
 9728.80 9761.16 9766.57 9779.09 9791.60 9803.94 9813.86 9864.31 9864.3110045.97
10053.5010054.3610067.3110067.3110079.3810091.9010154.4610166.9710179.4810303.17
10504.7610566.6210641.0410727.7410800.4110819.9410892.6010954.0711025.7711053.16
  246.15  246.05  246.69  247.88  248.62  248.84  249.73  248.95  248.94  249.42
  250.59  251.14  250.75  250.73  251.11  250.76  251.45  250.03  250.98  251.43
  251.52  250.77  251.71  251.95  251.65  252.19  252.14  252.86  252.49  253.12
  252.86  253.03  253.30  253.07  253.34  254.24  254.56  254.27  254.27  253.24
  256.44  256.47  255.89  255.89  254.98  254.53  254.78  255.22  254.97  255.08
  256.20  257.19  256.88  257.97  258.01  258.36  258.51  259.08  258.71  258.90
 -753.85 -753.95 -753.31 -752.12 -751.38 -751.16 -750.27 -751.05 -751.06 -750.58
 -749.41 -748.86 -749.25 -749.27 -748.89 -749.24 -748.55 -749.97 -749.02 -748.57
 -748.48 -749.23 -748.29 -748.05 -748.35 -747.81 -747.86 -747.14 -747.51 -746.88
 -747.14 -746.97 -746.70 -746.93 -746.66 -745.76 -745.44 -745.73  247.77  246.74
  249.94  249.97  249.39 -744.11 -745.02 -745.47 -745.22 -744.78 -745.03 -744.92
 -743.80 -742.81 -743.12 -742.03 -741.99 -741.64 -741.49 -740.92 -741.29 -741.10
 8923.15 8929.13 8942.98 8956.83 8970.68 9002.22 9016.67 9031.12 9039.93 9053.78
 9067.63 9081.49 9103.39 9136.89 9150.74 9164.59 9247.92 9275.05 9300.26 9325.47
 9343.42 9413.70 9425.56 9451.51 9491.27 9514.53 9556.98 9602.76 9655.55 9665.78
 9704.84 9728.80 9761.16 9766.57 9779.09 9791.60 9803.94 9813.86 9848.17 9848.17
10045.9710051.1710051.1710053.5010054.3610091.9010154.4610166.9710179.4810303.17
10504.7610566.6210641.0410727.7410800.4110819.9410892.6010954.0711025.7711053.16
  246.15  246.05  246.69  247.88  248.62  248.84  249.73  248.95  248.94  249.42
  250.59  251.14  250.75  250.73  251.11  250.76  251.45  250.03  250.98  251.43
  251.52  250.77  251.27  251.71  251.95  251.65  252.19  252.14  252.86  252.49
  253.12  252.86  253.03  253.30  253.07  253.34  254.24  254.56  254.37  254.37
  253.24  255.45  255.45  256.44  256.47  254.53  254.78  255.22  254.97  255.08
  256.20  257.19  256.88  257.97  258.01  258.36  258.51  259.08  258.71  258.90
 -753.85 -753.95 -753.31 -752.12 -751.38 -751.16 -750.27 -751.05 -751.06 -750.58
 -749.41 -748.86 -749.25 -749.27 -748.89 -749.24 -748.55 -749.97 -749.02 -748.57
 -748.48 -749.23 -748.73 -748.29 -748.05 -748.35 -747.81 -747.86 -747.14 -747.51
 -746.88 -747.14 -746.97 -746.70 -746.93 -746.66 -745.76 -745.44 -745.63  247.87
  246.74  248.95 -744.55 -743.56 -743.53 -745.47 -745.22 -744.78 -745.03 -744.92
 -743.80 -742.81 -743.12 -742.03 -741.99 -741.64 -741.49 -740.92 -741.29 -741.10
Pier Skew, UpSta & Num, DnSta & Num=  ,9965.81, 2 ,9949.67, 2 , 0 , 0 , 0 ,,
    4.00    4.00
 -746.30  253.70
    4.00    4.00
 -746.21  253.79
BR Coef=-1 , 0 , 0 ,, 0 ,,,0.8,0,1,0,
WSPro=,,,, 1 ,,,, 0 ,,,, 0 ,,,,-1 ,-1 ,-1 , 0 , 0 , 0 , 0 , 0
BC Design=,, 0 ,, 0 ,,,,,,

Type RM Length L Ch R = 1 ,30942.81,196.998000,196.998000,196.998000
XS GIS Cut Line= 6
787606.049706489802655.026811525787277.924706519802314.749033704
787083.480262011802193.221255928786241.466373146801556.068478152
 786071.32748422801479.679589272785807.438258638801394.585969693
#Sta/Elev= 30
 8905.87245.53399100.394247.79549253.136251.56399267.543249.9712 9382.03250.5476
9417.407247.00549452.784235.64239476.369236.60229488.162234.75899511.747 235.431
9566.787233.27549618.612 233.9539643.925237.76359702.863240.59489732.519236.6708
 9768.12238.43869795.801233.27839897.052240.59769947.678 230.5839998.303226.4549
10012.83227.253710029.15234.838210036.27236.435210061.78252.828310385.71254.8089
10663.86252.479411088.01 253.49811098.51253.757611119.51260.521311131.01260.3931
#Mann= 3 , 0 , 0
 8905.87    0.04       0 8905.87    0.04       011131.01    0.04       0
#XS Ineff= 2 , 0
       09826.917        10061.59       0
Bank Sta=8905.87,11131.01
Exp/Cntr=0.3,0.1

Type RM Length L Ch R = 1 ,30745.81,451.381900,451.381900,451.381900
XS GIS Cut Line= 6
787908.701239973802502.000662187787624.532368647802321.723161412
787241.671539773802132.454551842787117.036584113802059.691497746
787021.931066313801968.448921153786837.717996031801690.326488681
#Sta/Elev= 30
8825.608243.03558866.843243.07338907.178246.83438999.387248.0669 9161.84247.0851
9375.092250.20489486.006249.6245 9631.27251.79619700.485251.80199724.424250.1921
9762.034250.29159802.851242.43739844.389 237.6179857.532237.71399877.738235.4849
9894.468236.58889907.866 235.5439932.524236.54929957.028235.42979980.243229.1286
9998.014226.731110017.84225.991610029.68  230.2210041.44228.699710064.98234.0502
10076.75234.774210091.28246.549310100.29 251.26310159.13251.466310199.93249.9916
#Mann= 3 , 0 , 0
8825.608    0.04       08825.608    0.04       010199.93    0.04       0
#XS Ineff= 2 , 0
       09846.233                       0
Bank Sta=8825.608,10199.93
Exp/Cntr=0.3,0.1

Type RM Length L Ch R = 1 ,30294.43,451.381900,451.381900,451.381900
XS GIS Cut Line= 6
 788487.08355673802642.160012646788259.379720332802312.518694153
787991.061449777802040.279212608787670.992234893801798.942798733
787172.340220725801535.850355011786701.423929063801049.087668943
#Sta/Elev= 30
8390.978246.73048527.267245.35028712.128 249.4848842.512242.19919032.618243.7566
9088.268 248.9829101.905244.26079198.622242.87939373.316248.08859423.107246.1298
9474.773236.19759606.451244.89369722.357242.23289768.045235.09259835.792237.0761
9858.122232.29749968.343233.73759989.996224.367110000.82223.709210106.33 230.694
10238.43227.912210333.95230.499710371.18225.397310399.59238.588110427.99 239.391
10497.22253.013110658.07255.015210710.11250.009510774.09258.220810820.05 252.854
#Mann= 3 , 0 , 0
8390.978  0.0454       08390.978  0.0454       010820.05  0.0454       0
#XS Ineff= 2 , 0
       09884.105        10368.05       0
Bank Sta=8390.978,10820.05
Exp/Cntr=0.3,0.1

Type RM Length L Ch R = 1 ,29843.05,451.381900,451.381900,451.381900
XS GIS Cut Line= 6
788562.477268431802545.042689107788291.262246628 802081.13222866
787728.031347816801351.286874707787581.423391629801231.491407171
787258.590035823801092.349071082787019.220019074800861.765046974
#Sta/Elev= 30
8208.347246.14648489.714248.42848608.438243.10998740.359243.53428754.494247.0442
8774.427247.48098804.064243.6891 8966.24241.72829078.919243.4431 9141.65241.9385
9224.749230.59979279.237230.77249391.915237.20699457.428231.96319479.874 226.674
9505.595228.53349544.177 221.6799701.506226.67359755.963223.17099921.316228.2029
10015.38220.649510037.78223.061510057.65231.275910068.38232.682910216.93229.7106
 10274.5251.511610305.83258.173210350.85257.630110407.39261.558210545.92260.4868
#Mann= 3 , 0 , 0
8208.347  0.0424       08208.347  0.0424       010545.92  0.0424       0
#XS Ineff= 2 , 0
       09559.337                       0
Bank Sta=8208.347,10545.92
Exp/Cntr=0.3,0.1

Type RM Length L Ch R = 1 ,29391.66,275.781300,275.781300,275.781300
XS GIS Cut Line= 6
788573.406409407802530.964473613788403.860170718802202.303447874
787899.315239745801411.609005573787833.904852288801232.191469625
787766.310191171 800822.05995689787673.668833594800476.004895311
#Sta/Elev= 30
8250.662246.35568513.336247.64478641.658243.39428665.509247.9816 8689.36244.2769
9150.177241.14839170.036243.00039351.888230.41939386.439235.38329432.355233.9049
9455.313230.30799511.497230.12229559.963219.21799588.903223.03029758.532229.1853
9778.988223.0014 9840.06226.1873 9860.29223.57589920.732225.37169991.498219.5599
10011.96 219.65410032.37225.4987 10072.9222.702710174.32221.681310194.82226.1972
10215.32234.892610349.24  239.4410359.61244.081510390.71266.245710525.49265.3856
#Mann= 3 , 0 , 0
8250.662  0.0494       08250.662  0.0494       010525.49  0.0494       0
#XS Ineff= 2 , 0
       09586.851                       0
Bank Sta=8250.662,10525.49
Exp/Cntr=0.3,0.1