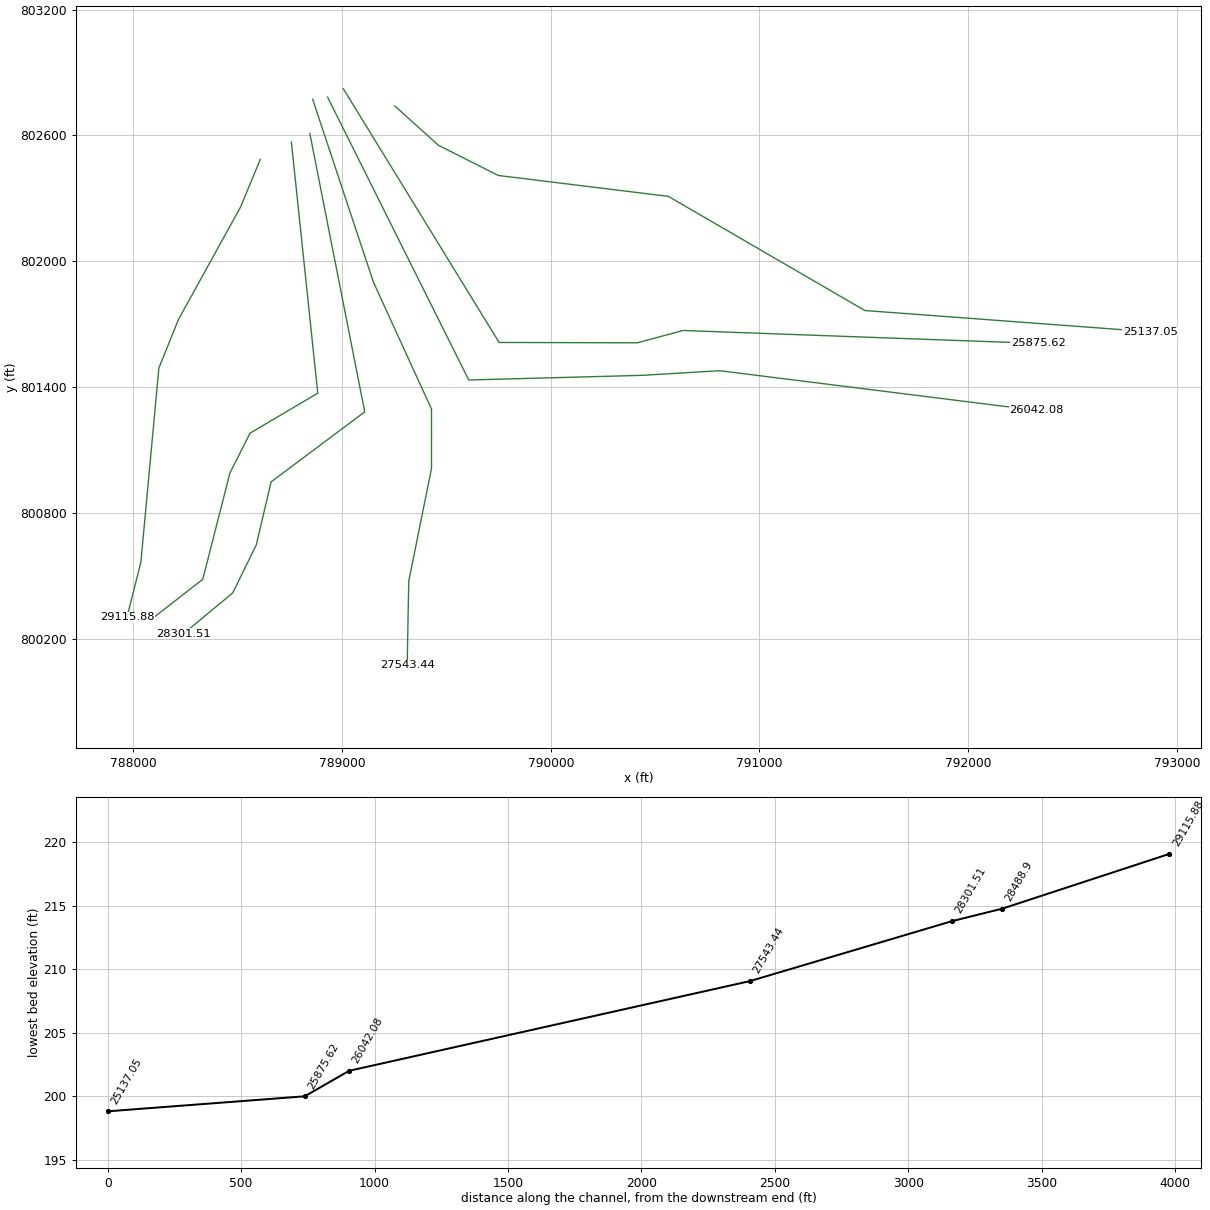
HEC-RAS study 17646_ras.prj: 17646

--- 17646_ras.g01 (geometry) --- (continued)

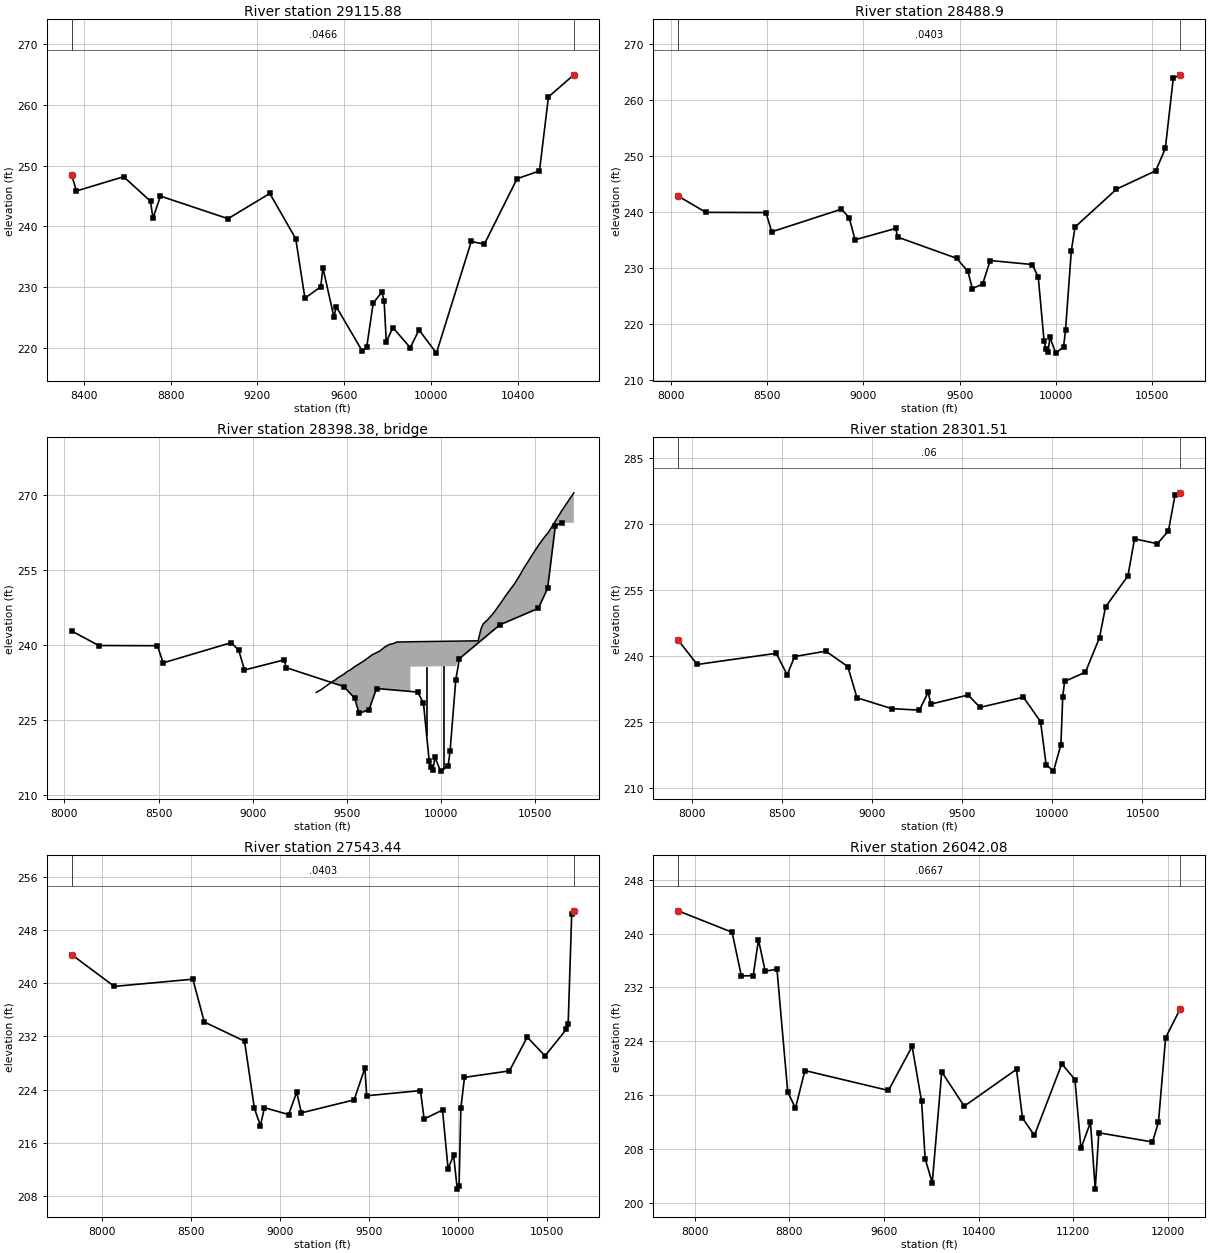
Type RM Length L Ch R = 1 ,29115.88,626.982500,626.982500,626.982500
XS GIS Cut Line= 6
788608.443171799802485.832372949788513.525586724802258.225816369
788216.762756705801723.415394977788122.444977432801490.887252197
788036.181995243800565.051262021787969.455140309800301.655781971
#Sta/Elev= 30
 8344.38248.43678366.595245.8109  8583.7248.15458707.436244.11598718.703241.3227
8753.254 244.9659064.238241.24359256.683245.39569376.146237.93689418.477228.1403
9491.138230.01889501.434233.12239552.235224.98429562.306226.76249682.775 219.408
9702.836220.03439732.926227.36369773.047229.13949783.078227.64979793.108220.9431
9823.199223.3088 9903.44219.98589943.561222.9153 10023.8219.088110184.29237.4861
10244.47237.041210395.21  247.8310498.37249.112210539.63261.306810656.56264.9483
#Mann= 3 , 0 , 0
 8344.38  0.0466       0 8344.38  0.0466       010656.56  0.0466       0
#XS Ineff= 2 , 0
       09670.963                       0
Bank Sta=8344.38,10656.56
Exp/Cntr=0.3,0.1

Type RM Length L Ch R = 1 , 28488.9,187.387700,187.387700,187.387700
XS GIS Cut Line= 6
788757.240187913802568.368599117788883.665609062 801370.78616789
788559.174706459801180.200422615788462.482625395800989.427509174
788332.881323904800483.365284368788106.049706489800307.804589272
#Sta/Elev= 30
8038.385242.8182 8182.55239.91148494.273239.8753 8524.44236.4368 8886.44240.4862
8926.662238.93848956.829235.01069167.996237.04549178.052235.48779484.617231.7027
9542.604229.35179565.798226.30739618.943227.09339658.407231.30549877.689230.5948
9907.986228.32249938.284216.86139948.383215.50979958.482214.96919968.581217.5752
9998.879 214.76810039.28215.887310049.37218.820310079.67233.086510098.99237.2948
10313.93244.054510518.11  247.3510567.55251.3362 10608.9263.882610645.32264.4771
#Mann= 3 , 0 , 0
8038.385  0.0403       08038.385  0.0403       010645.32  0.0403       0
#XS Ineff= 2 , 0
       09782.424        10136.86       0
Bank Sta=8038.385,10645.32
Exp/Cntr=0.3,0.1

Type RM Length L Ch R = 3 ,28398.38,,,
BEGIN DESCRIPTION:
END DESCRIPTION:
Bridge Culvert--1,0,-1,-1, 0
Deck Dist Width WeirC Skew NumUp NumDn MinLoCord MaxHiCord MaxSubmerge Is_Ogee
63.193850,61.000000,2.6,0, 36, 36, , , 0.95, 0, 0,0,,
 9337.87 9363.35 9429.51 9440.54 9453.71 9484.65 9501.15 9517.74 9539.79 9587.83
 9637.48 9674.71 9699.53 9724.35 9744.69 9767.62 9838.62 9838.6210098.6210098.62
10198.3010214.4210225.2410246.8610279.2910322.5310344.1610392.7510423.6610437.82
10491.3310524.7110554.4910572.3110643.8410706.94
  230.54  231.06  232.84  233.05  233.47  234.16  234.67  234.99  235.62  236.75
  238.10  238.78  239.53  240.09  240.27  240.61  240.67  240.67  240.80  240.80
  240.86  243.34  244.25  244.99  246.37  248.63  249.86  252.33  254.23  255.19
  258.39  260.30  261.79  262.60  266.96  270.48
 -769.46 -768.94 -767.16 -766.95 -766.53 -765.84 -765.33 -765.01 -764.38 -763.25
 -761.90 -761.22 -760.47 -759.91 -759.73 -759.39 -759.33  235.67  235.80 -759.20
 -759.14 -756.66 -755.75 -755.01 -753.63 -751.37 -750.14 -747.67 -745.77 -744.81
 -741.61 -739.70 -738.21 -737.40 -733.04 -729.52
 9337.87 9363.35 9429.51 9440.54 9453.71 9484.65 9501.15 9517.74 9539.79 9587.83
 9637.48 9674.71 9699.53 9724.35 9744.69 9767.62 9867.52 9867.5210127.5210127.52
10198.3010214.4210225.2410246.8610279.2910322.5310344.1610392.7510423.6610437.82
10491.3310524.7110554.4910572.3110643.8410706.94
  230.54  231.06  232.84  233.05  233.47  234.16  234.67  234.99  235.62  236.75
  238.10  238.78  239.53  240.09  240.27  240.61  240.68  240.68  240.82  240.82
  240.86  243.34  244.25  244.99  246.37  248.63  249.86  252.33  254.23  255.19
  258.39  260.30  261.79  262.60  266.96  270.48
 -769.46 -768.94 -767.16 -766.95 -766.53 -765.84 -765.33 -765.01 -764.38 -763.25
 -761.90 -761.22 -760.47 -759.91 -759.73 -759.39 -759.32  235.68  235.82 -759.18
 -759.14 -756.66 -755.75 -755.01 -753.63 -751.37 -750.14 -747.67 -745.77 -744.81
 -741.61 -739.70 -738.21 -737.40 -733.04 -729.52
Pier Skew, UpSta & Num, DnSta & Num=  ,9924.62, 2 ,9953.52, 2 , 0 , 0 , 0 ,,
    4.00    4.00
 -759.29  240.71
    4.00    4.00
 -759.27  240.73
Pier Skew, UpSta & Num, DnSta & Num=  ,10012.62, 2 ,10041.52, 2 , 0 , 0 , 0 ,,
    4.00    4.00
 -759.24  240.76
    4.00    4.00
 -759.23  240.77
BR Coef=-1 , 0 , 0 ,, 0 ,,,0.8,0,1,0,
WSPro=,,,, 1 ,,,, 0 ,,,, 0 ,,,,-1 ,-1 ,-1 , 0 , 0 , 0 , 0 , 0
BC Design=,, 0 ,, 0 ,,,,,,

Type RM Length L Ch R = 1 ,28301.51,758.072800,758.072800,758.072800
XS GIS Cut Line= 6
788845.671853065  802609.1832138789108.653873146801281.762922615
788659.970322907800947.769947976788588.998181581 800646.90978384
788476.368479133800418.564633623788241.466373146800224.471255943
#Sta/Elev= 30
7921.875243.54178028.083238.0161 8466.44240.55048527.606235.65958568.384239.8108
8741.688 241.038 8864.02237.54388914.992230.44979108.685227.9762  9261.6227.6414
 9310.12231.72369324.927229.01249532.067231.08129598.079228.26619838.779230.5814
9934.096225.04519964.919215.274910006.02213.790410047.11219.799110057.39 230.716
10067.66234.159610183.48236.265510261.53244.121910294.98251.084610419.18258.1403
10456.05266.548610582.87265.444310644.29268.365410681.15 276.58410710.06276.9994
#Mann= 3 , 0 , 0
7921.875    0.06       07921.875    0.06       010710.06    0.06       0
#XS Ineff= 2 , 0
       09805.994        10093.23       0
Bank Sta=7921.875,10710.06
Exp/Cntr=0.3,0.1

Type RM Length L Ch R = 1 ,27543.44,1501.362200,1501.362200,1501.362200
XS GIS Cut Line= 6
788859.276724547802772.441672519 789150.40729022801900.038602605
789428.598971367801295.061673865789428.530157596801011.908892229
789319.503002107800473.933222666789312.077902824800073.024755165
#Sta/Elev= 30
7826.607244.28488066.378239.51468508.088240.5962  8572.4234.16788798.691231.2848
 8853.94221.20218887.917218.59988910.568221.29499046.474 220.2649091.776223.6113
9118.219220.51849414.703222.46649475.305227.24669485.334 223.0869787.707223.8587
9808.189219.59299911.831220.94439942.941212.11859974.051214.15419994.583209.0612
10004.73209.5568 10014.9221.236110035.25225.850310287.87226.818210388.04231.8981
10488.05229.070910608.07233.067910618.07233.811410638.07250.395510650.05250.8672
#Mann= 3 , 0 , 0
7826.607  0.0403       07826.607  0.0403       010650.05  0.0403       0
#XS Ineff= 2 , 0
       09811.815        10063.64       0
Bank Sta=7826.607,10650.05
Exp/Cntr=0.3,0.1

Type RM Length L Ch R = 1 ,26042.08,166.457500,166.457500,166.457500
XS GIS Cut Line= 5
 788930.70230031802782.645326197789606.987916678801433.739187613
790440.056531191801455.996745989790809.737222642801478.028462633
792328.271928668801288.707367063
#Sta/Elev= 30
7861.034243.39418316.867240.20778395.348233.70938495.365233.75618539.989239.0834
8596.703 234.4158696.175234.71058786.873216.4929 8852.36214.02338932.296219.6347
9638.085216.67379838.156223.22639918.185215.03249948.195 206.50810008.22202.9313
10088.25 219.42810278.42214.337210720.07219.816510770.45212.569110871.23209.9899
11103.01220.628511213.86218.298811264.25208.049611344.87211.919311385.18 201.997
11415.41210.378211868.89209.009511919.28211.944411979.74224.513112103.97228.8436
#Mann= 3 , 0 , 0
7861.034  0.0667       07861.034  0.0667       012103.97  0.0667       0
#XS Ineff= 2 , 0
       09868.448        10116.28       0
Bank Sta=7861.034,12103.97
Exp/Cntr=0.3,0.1

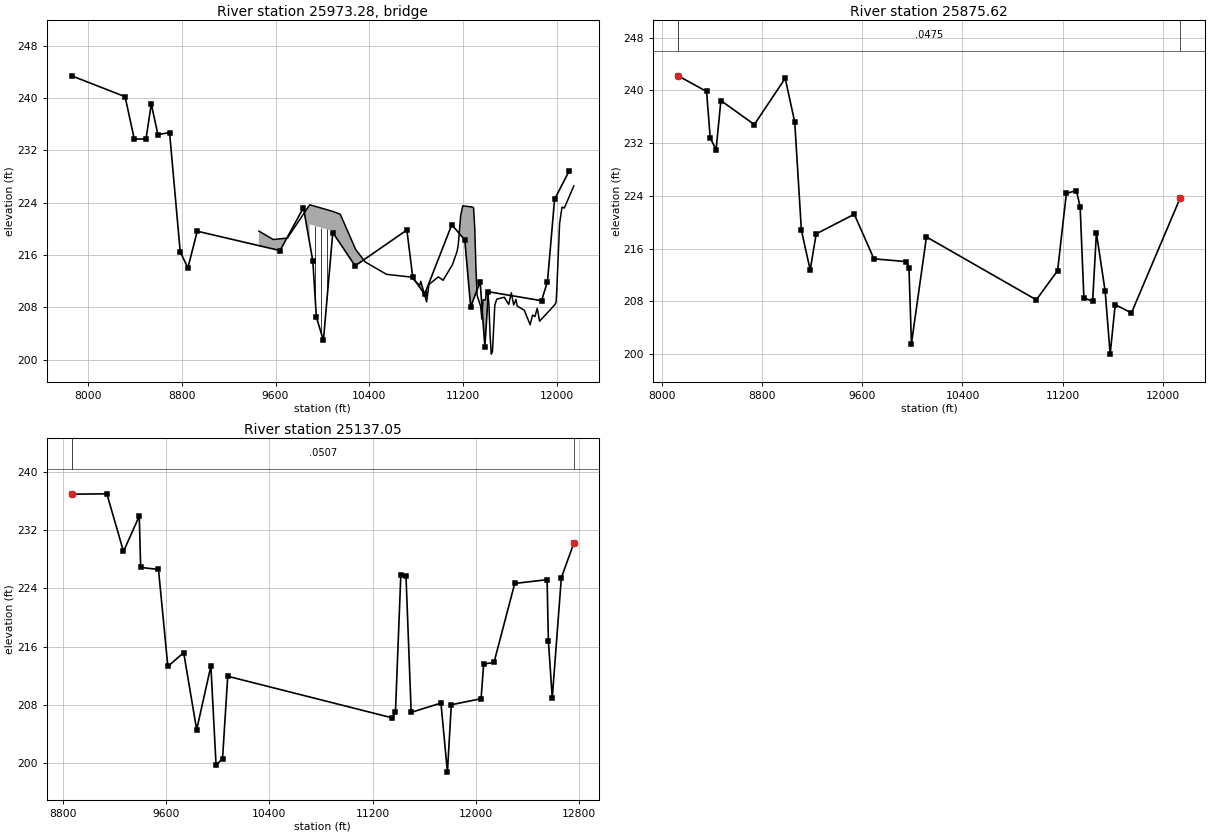
Type RM Length L Ch R = 3 ,25973.28,,,
BEGIN DESCRIPTION:
END DESCRIPTION:
Bridge Culvert--1,0,-1,-1, 0
Deck Dist Width WeirC Skew NumUp NumDn MinLoCord MaxHiCord MaxSubmerge Is_Ogee
42.228750,82.000000,2.6,0, 60, 60, , , 0.95, 0, 0,0,,
 9458.06 9581.17 9701.17 9891.00 9891.00 9891.2810087.0010087.0010151.9610282.89
10363.8810546.5510758.1710828.2810838.2910888.3710908.4010988.5211028.5811108.69
11148.7511158.7711178.8011197.2111281.6311289.2711299.3111309.3611319.4111349.56
11359.6011369.6511389.7511399.8011409.8411419.8911429.9411439.9911450.0411470.13
11486.2211550.5211588.5211610.8111630.9011651.0011661.0511721.3411771.5811791.67
11811.7711831.8711851.9611982.5911992.6411997.7012022.7812042.8812062.9712144.08
  219.65  218.36  218.59  223.67  223.67  223.68  222.67  222.67  222.23  216.86
  214.94  213.04  212.62  211.33  211.98  208.83  211.49  212.65  212.13  214.51
  216.58  217.63  222.04  223.52  223.32  223.18  219.97  213.80  209.81  208.12
  206.20  209.15  209.09  210.45  210.44  208.34  203.62  200.84  201.22  208.31
  209.24  209.54  208.44  210.22  208.36  209.20  208.18  207.56  205.32  206.81
  206.58  207.84  205.88  208.40  208.79  210.26  220.83  223.31  223.18  226.57
 -780.35 -781.64 -781.41 -776.33  220.67  220.68  219.67 -777.33 -777.77 -783.14
 -785.06 -786.96 -787.38 -788.67 -788.02 -791.17 -788.51 -787.35 -787.87 -785.49
 -783.42 -782.37 -777.96 -776.48 -776.68 -776.82 -780.03 -786.20 -790.19 -791.88
 -793.80 -790.85 -790.91 -789.55 -789.56 -791.66 -796.38 -799.16 -798.78 -791.69
 -790.76 -790.46 -791.56 -789.78 -791.64 -790.80 -791.82 -792.44 -794.68 -793.19
 -793.42 -792.16 -794.12 -791.60 -791.21 -789.74 -779.17 -776.69 -776.82 -773.43
 9458.06 9581.17 9701.17 9861.20 9922.19 9922.1910118.1910118.1910151.9610282.89
10363.8810546.5510758.1710828.2810838.2910888.3710908.4010988.5211028.5811108.69
11148.7511158.7711178.8011197.2111281.6311289.2711299.3111309.3611319.4111349.56
11359.6011369.6511389.7511399.8011409.8411419.8911429.9411439.9911450.0411470.13
11486.2211550.5211588.5211610.8111630.9011651.0011661.0511721.3411771.5811791.67
11811.7711831.8711851.9611982.5911992.6411997.7012022.7812042.8812062.9712144.08
  219.65  218.36  218.59  223.10  223.23  223.23  222.56  222.56  222.23  216.86
  214.94  213.04  212.62  211.33  211.98  208.83  211.49  212.65  212.13  214.51
  216.58  217.63  222.04  223.52  223.32  223.18  219.97  213.80  209.81  208.12
  206.20  209.15  209.09  210.45  210.44  208.34  203.62  200.84  201.22  208.31
  209.24  209.54  208.44  210.22  208.36  209.20  208.18  207.56  205.32  206.81
  206.58  207.84  205.88  208.40  208.79  210.26  220.83  223.31  223.18  226.57
 -780.35 -781.64 -781.41 -776.90 -776.77  220.23  219.56 -777.44 -777.77 -783.14
 -785.06 -786.96 -787.38 -788.67 -788.02 -791.17 -788.51 -787.35 -787.87 -785.49
 -783.42 -782.37 -777.96 -776.48 -776.68 -776.82 -780.03 -786.20 -790.19 -791.88
 -793.80 -790.85 -790.91 -789.55 -789.56 -791.66 -796.38 -799.16 -798.78 -791.69
 -790.76 -790.46 -791.56 -789.78 -791.64 -790.80 -791.82 -792.44 -794.68 -793.19
 -793.42 -792.16 -794.12 -791.60 -791.21 -789.74 -779.17 -776.69 -776.82 -773.43
Pier Skew, UpSta & Num, DnSta & Num=  ,9939.25, 2 ,9970.44, 2 , 0 , 0 , 0 ,,
    3.00    3.00
 -776.83  223.17
    3.00    3.00
 -776.94  223.06
Pier Skew, UpSta & Num, DnSta & Num=  ,9989.00, 2 ,10020.19, 2 , 0 , 0 , 0 ,,
    3.00    3.00
 -777.00  223.00
    3.00    3.00
 -777.11  222.89
Pier Skew, UpSta & Num, DnSta & Num=  ,10038.75, 2 ,10069.94, 2 , 0 , 0 , 0 ,,
    3.00    3.00
 -777.17  222.83
    3.00    3.00
 -777.28  222.72
BR Coef=-1 , 0 , 0 ,, 0 ,,,0.8,0,1,0,
WSPro=,,,, 1 ,,,, 0 ,,,, 0 ,,,,-1 ,-1 ,-1 , 0 , 0 , 0 , 0 , 0
BC Design=,, 0 ,, 0 ,,,,,,

Type RM Length L Ch R = 1 ,25875.62,738.572400,738.572400,738.572400
XS GIS Cut Line= 5
789005.529093862802823.459940866789752.598223507801612.673290536
790414.476687163801611.074550271790634.045582771801669.836873427
792335.216373146 801608.15181151
#Sta/Elev= 30
8126.839242.22568354.358239.85168383.536232.79068430.534231.02738468.622 238.472
8736.046234.83228982.809241.84969058.984235.19939112.057218.83449182.559212.7429
 9230.38 218.2379535.069221.21739691.955214.44769951.956214.02989971.956213.0831
9991.956201.591210111.96 217.77510990.05208.227111160.16212.6616 11230.2224.3759
11310.26224.817311340.28222.3446 11370.3 208.50711440.34208.029411470.36218.3723
11540.41 209.52911580.43199.987111620.46207.492711750.55206.247312141.02223.7286
#Mann= 3 , 0 , 0
8126.839  0.0475       08126.839  0.0475       012141.02  0.0475       0
#XS Ineff= 2 , 0
       09903.201        10145.17       0
Bank Sta=8126.839,12141.02
Exp/Cntr=0.3,0.1

Type RM Length L Ch R = 1 ,25137.05,1130.386900,1130.386900,1130.386900
XS GIS Cut Line= 6
789253.107635002 802740.21286871789461.687106538802553.003127084
789748.641005187802409.051688416790563.302078626802309.463770542
791504.950313568          801765792871.674706489801663.707367063
#Sta/Elev= 30
8868.967236.92799141.693236.97689270.623229.06949392.721 233.9169403.586226.8782
9541.593226.60629614.279213.29659736.849215.19579837.484204.62149947.571213.3591
9987.736199.750310037.94200.666810078.09211.953811354.17206.238511377.35207.0373
11419.02225.846411459.13 225.67711499.24206.997811729.87208.2777   11780198.8038
11810.09208.048512040.72208.872612060.77213.621112140.99213.853412301.43224.6847
12552.12225.199612562.14216.814212592.23208.973812662.42225.454312759.36230.2217
#Mann= 3 , 0 , 0
8868.967  0.0507       08868.967  0.0507       012759.36  0.0507       0
#XS Ineff= 2 , 0
       09837.298        10445.39       0
Bank Sta=8868.967,12759.36
Exp/Cntr=0.3,0.1