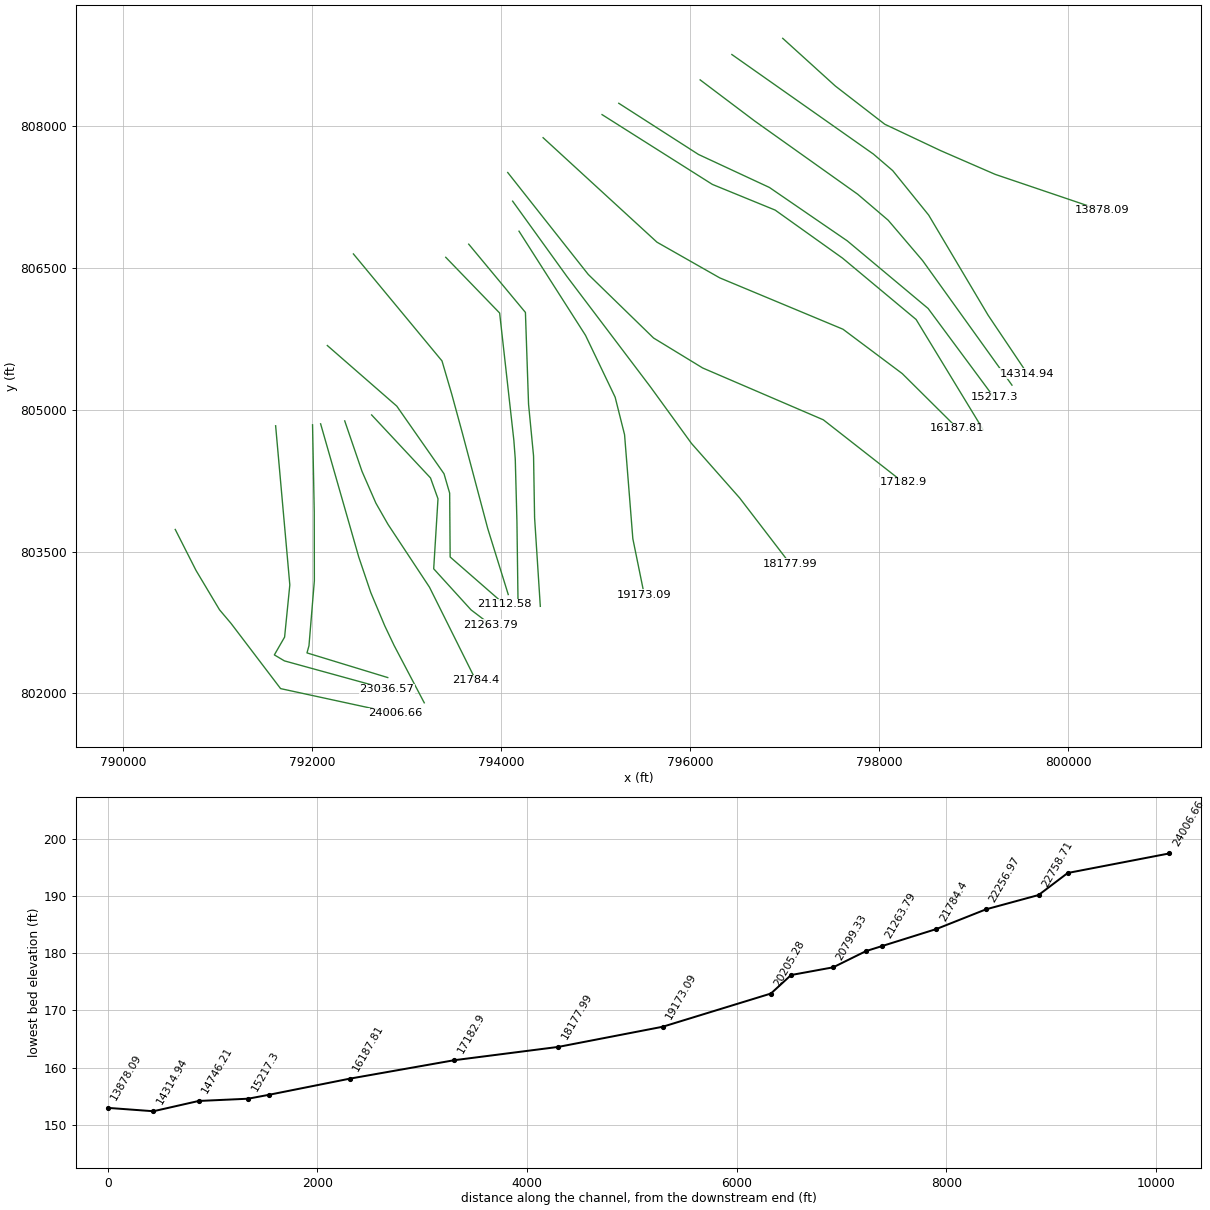
HEC-RAS study 17646_ras.prj: 17646

--- 17646_ras.g01 (geometry) --- (continued)

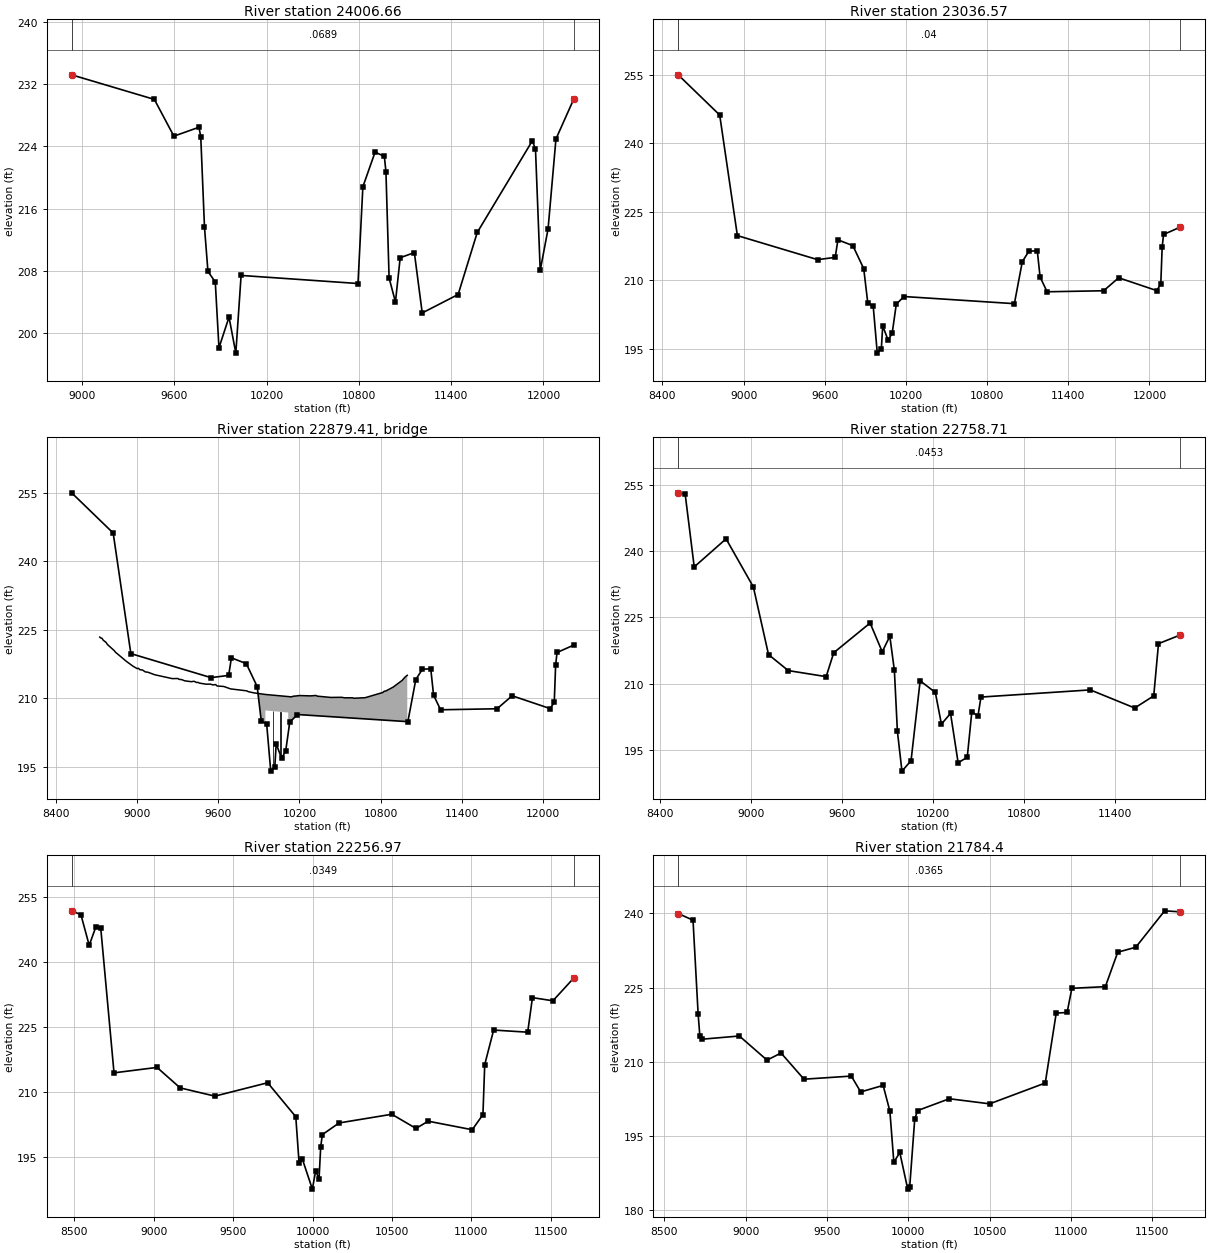
Type RM Length L Ch R = 1 ,24006.66,970.092800,970.092800,970.092800
XS GIS Cut Line= 6
790554.661692479803733.383437081790774.517564134803299.703463608
791022.781043813802883.951523433791144.251637737802740.268040126
791668.960462075 802049.86594371792878.356103748801787.865616202
#Sta/Elev= 30
8933.068 233.2199470.681230.05619597.569225.32629760.597226.47419772.273225.2485
9796.478213.63699818.979207.91589866.659206.56879890.525198.08879955.935202.0455
10000.14197.410510034.49207.406310794.23206.3672   10826218.815410905.42223.2741
10965.59222.721110975.89220.750110996.49207.083711037.68203.990411068.58209.6882
11160.62210.344411211.75202.5807 11445.1204.953211569.66212.947311927.56224.7306
11948.01223.641911978.69208.052312029.82 213.40712080.95224.960812196.87230.1078
#Mann= 3 , 0 , 0
8933.068  0.0689       08933.068  0.0689       012196.87  0.0689       0
#XS Ineff= 2 , 0
       09635.908        10335.34       0
Bank Sta=8933.068,12196.87
Exp/Cntr=0.3,0.1

Type RM Length L Ch R = 1 ,23036.57,277.862100,277.862100,277.862100
XS GIS Cut Line= 6
791616.466373116804830.374033704791766.626923889803147.116634563
791711.398061842802594.828014076791603.103578538802406.552484885
 791709.35254842802343.229864746792794.181019604 802044.59962295
#Sta/Elev= 30
8516.722255.0031 8823.62246.19118954.269219.75669546.936 214.4889677.322214.9817
9697.381218.83379807.708217.55289887.945212.52729918.035205.00459958.153204.3033
9988.242193.992910018.33195.001610028.36199.963110068.48196.829810098.57198.3864
10128.66204.716510185.61206.402911001.58204.835411060.18 214.05711108.56216.3178
11170.79216.442511191.54210.6716 11243.4207.4412 11661.2207.667311772.37210.5121
12052.41207.712812083.53209.0614 12093.9217.319912104.27 220.00212227.88221.6229
#Mann= 3 , 0 , 0
8516.722    0.04       08516.722    0.04       012227.88    0.04       0
#XS Ineff= 2 , 0
       0 9875.08        10216.66       0
Bank Sta=8516.722,12227.88
Exp/Cntr=0.3,0.1

Type RM Length L Ch R = 3 ,22879.41,,,
BEGIN DESCRIPTION:
END DESCRIPTION:
Bridge Culvert--1,0,-1,-1, 0
Deck Dist Width WeirC Skew NumUp NumDn MinLoCord MaxHiCord MaxSubmerge Is_Ogee
80.431050,117.000000,2.6,0, 60, 60, , , 0.95, 0, 0,0,,
 8724.49 8730.63 8740.64 8750.64 8770.66 8780.66 8830.70 8840.70 8920.75 8970.79
 9000.81 9010.81 9020.82 9040.83 9060.85 9080.86 9130.89 9260.98 9301.00 9311.01
 9331.02 9351.04 9401.07 9421.08 9441.09 9451.10 9461.11 9511.14 9541.16 9561.17
 9581.19 9591.19 9641.23 9691.26 9811.40 9821.42 9861.49 9948.59 9948.5910117.59
10117.5910142.0310152.0510202.1310282.2410322.7210332.3110432.4110512.4910532.51
10592.5710602.7510685.8110815.9910826.9810837.9610892.8910958.7910980.7610997.27
  223.38  223.20  223.12  222.68  222.23  221.77  220.43  220.06  218.07  216.98
  216.47  216.53  216.23  216.15  215.75  215.67  215.12  214.27  214.30  214.11
  214.05  213.80  213.60  213.69  213.42  213.45  213.29  213.05  213.07  212.89
  212.97  212.66  212.55  212.02  211.59  211.42  211.16  210.80  210.80  210.34
  210.34  210.27  210.40  210.56  210.49  210.58  210.43  210.15  210.18  210.07
  210.07  209.97  210.09  211.23  211.51  211.55  212.41  213.87  214.61  215.00
 -776.62 -776.80 -776.88 -777.32 -777.77 -778.23 -779.57 -779.94 -781.93 -783.02
 -783.53 -783.47 -783.77 -783.85 -784.25 -784.33 -784.88 -785.73 -785.70 -785.89
 -785.95 -786.20 -786.40 -786.31 -786.58 -786.55 -786.71 -786.95 -786.93 -787.11
 -787.03 -787.34 -787.45 -787.98 -788.41 -788.58 -788.84 -789.20  207.30  206.84
 -789.66 -789.73 -789.60 -789.44 -789.51 -789.42 -789.57 -789.85 -789.82 -789.93
 -789.93 -790.03 -789.91 -788.77 -788.49 -788.45 -787.59 -786.13 -785.39 -785.00
 8724.49 8730.63 8740.64 8750.64 8770.66 8780.66 8830.70 8840.70 8920.75 8970.79
 9000.81 9010.81 9020.82 9040.83 9060.85 9080.86 9130.89 9260.98 9301.00 9311.01
 9331.02 9351.04 9401.07 9421.08 9441.09 9451.10 9461.11 9511.14 9541.16 9561.17
 9581.19 9591.19 9641.23 9691.26 9811.40 9821.42 9861.49 9938.78 9938.7810107.78
10107.7810142.0310152.0510202.1310282.2410322.7210332.3110432.4110512.4910532.51
10592.5710602.7510685.8110815.9910826.9810837.9610892.8910958.7910980.7610997.27
  223.38  223.20  223.12  222.68  222.23  221.77  220.43  220.06  218.07  216.98
  216.47  216.53  216.23  216.15  215.75  215.67  215.12  214.27  214.30  214.11
  214.05  213.80  213.60  213.69  213.42  213.45  213.29  213.05  213.07  212.89
  212.97  212.66  212.55  212.02  211.59  211.42  211.16  210.82  210.82  210.36
  210.36  210.27  210.40  210.56  210.49  210.58  210.43  210.15  210.18  210.07
  210.07  209.97  210.09  211.23  211.51  211.55  212.41  213.87  214.61  215.00
 -776.62 -776.80 -776.88 -777.32 -777.77 -778.23 -779.57 -779.94 -781.93 -783.02
 -783.53 -783.47 -783.77 -783.85 -784.25 -784.33 -784.88 -785.73 -785.70 -785.89
 -785.95 -786.20 -786.40 -786.31 -786.58 -786.55 -786.71 -786.95 -786.93 -787.11
 -787.03 -787.34 -787.45 -787.98 -788.41 -788.58 -788.84 -789.18  207.32  206.86
 -789.64 -789.73 -789.60 -789.44 -789.51 -789.42 -789.57 -789.85 -789.82 -789.93
 -789.93 -790.03 -789.91 -788.77 -788.49 -788.45 -787.59 -786.13 -785.39 -785.00
Pier Skew, UpSta & Num, DnSta & Num=  ,10004.26, 2 ,9994.45, 2 , 0 , 0 , 0 ,,
    4.00    4.00
 -789.35  210.65
    4.00    4.00
 -789.33  210.67
Pier Skew, UpSta & Num, DnSta & Num=  ,10061.92, 2 ,10052.11, 2 , 0 , 0 , 0 ,,
    4.00    4.00
 -789.51  210.49
    4.00    4.00
 -789.48  210.52
BR Coef=-1 , 0 , 0 ,, 0 ,,,0.8,0,1,0,
WSPro=,,,, 1 ,,,, 0 ,,,, 0 ,,,,-1 ,-1 ,-1 , 0 , 0 , 0 , 0 , 0
BC Design=,, 0 ,, 0 ,,,,,,

Type RM Length L Ch R = 1 ,22758.71,501.731700,501.731700,501.731700
XS GIS Cut Line= 6
792007.091373116804840.790700376792025.067977739803920.202975812
792026.224889172 803190.93871537791969.265194684802503.353831708
791948.221423656802427.596255943792802.598527998802166.653494999
#Sta/Elev= 30
 8517.34253.2295 8563.14253.03028623.151236.43598833.191242.80029013.226231.8954
9113.245216.56499243.269212.93739493.307211.56639543.307216.98099783.307223.7177
9863.307217.18959913.307220.72919943.307212.99179963.307199.14899993.307 190.146
10053.31192.512710113.31210.619510213.47207.9797 10253.6200.800110313.81203.2285
10363.98192.017710424.19193.325910454.29 203.65810494.43202.592610514.49206.9336
11235.79208.557811528.56204.458211654.03207.2062 11685.4219.038611829.27221.0112
#Mann= 3 , 0 , 0
 8517.34  0.0453       0 8517.34  0.0453       011829.27  0.0453       0
#XS Ineff= 2 , 0
       0 9878.19        10203.04       0
Bank Sta=8517.34,11829.27
Exp/Cntr=0.3,0.1

Type RM Length L Ch R = 1 ,22256.97,472.575500,472.575500,472.575500
XS GIS Cut Line= 6
792092.413719353804851.104390583792495.841968852803441.866316605
 792623.18486788803065.574967691792770.637479022802714.731856372
792869.400905597802507.079073706793188.729330609801899.730246671
#Sta/Elev= 30
8484.106251.77628542.514250.87498594.567 243.831 8636.21248.04298667.442247.7122
8750.727214.44389021.405215.69419167.154210.97269385.401209.07689717.744212.1583
9894.648204.32559915.469193.61629936.291 194.5419998.895187.648610019.89 191.894
10040.88189.942710051.38197.380110061.88200.213610167.11202.897410498.87204.8991
10651.15201.634510727.94203.302211005.11201.333311072.45204.824811083.67216.3506
11139.79224.3008   11354223.810711383.99231.775911512.76231.045811644.11236.2926
#Mann= 3 , 0 , 0
8484.106  0.0349       08484.106  0.0349       011644.11  0.0349       0
#XS Ineff= 2 , 0
       09771.645        10124.26       0
Bank Sta=8484.106,11644.11
Exp/Cntr=0.3,0.1

Type RM Length L Ch R = 1 , 21784.4,520.608600,520.608600,520.608600
XS GIS Cut Line= 6
792347.467129216804881.935022553792529.993745729804348.835429947
792676.905511127804012.304021438792804.486160918803788.559005801
793244.469063578803122.081327173793734.308297122802138.216860775
#Sta/Elev= 30
8585.107239.97768676.377238.62588707.873219.59438718.372215.2031 8728.87214.5414
8961.204215.19549131.405210.31249217.475211.75639358.478206.45699649.467207.0876
9707.248203.88029845.104205.20599886.505199.99449910.892189.65969947.472191.6298
9996.247184.216810008.44184.687110039.17198.337710056.54200.102110251.74202.5027
10499.93201.474410841.61205.684610909.09219.826910976.05 219.95811005.27224.8458
11211.13225.1805 11287.3232.146811398.21233.156411575.67240.520911671.92240.3169
#Mann= 3 , 0 , 0
8585.107  0.0365       08585.107  0.0365       011671.92  0.0365       0
#XS Ineff= 2 , 0
       09751.119        10095.22       0
Bank Sta=8585.107,11671.92
Exp/Cntr=0.3,0.1

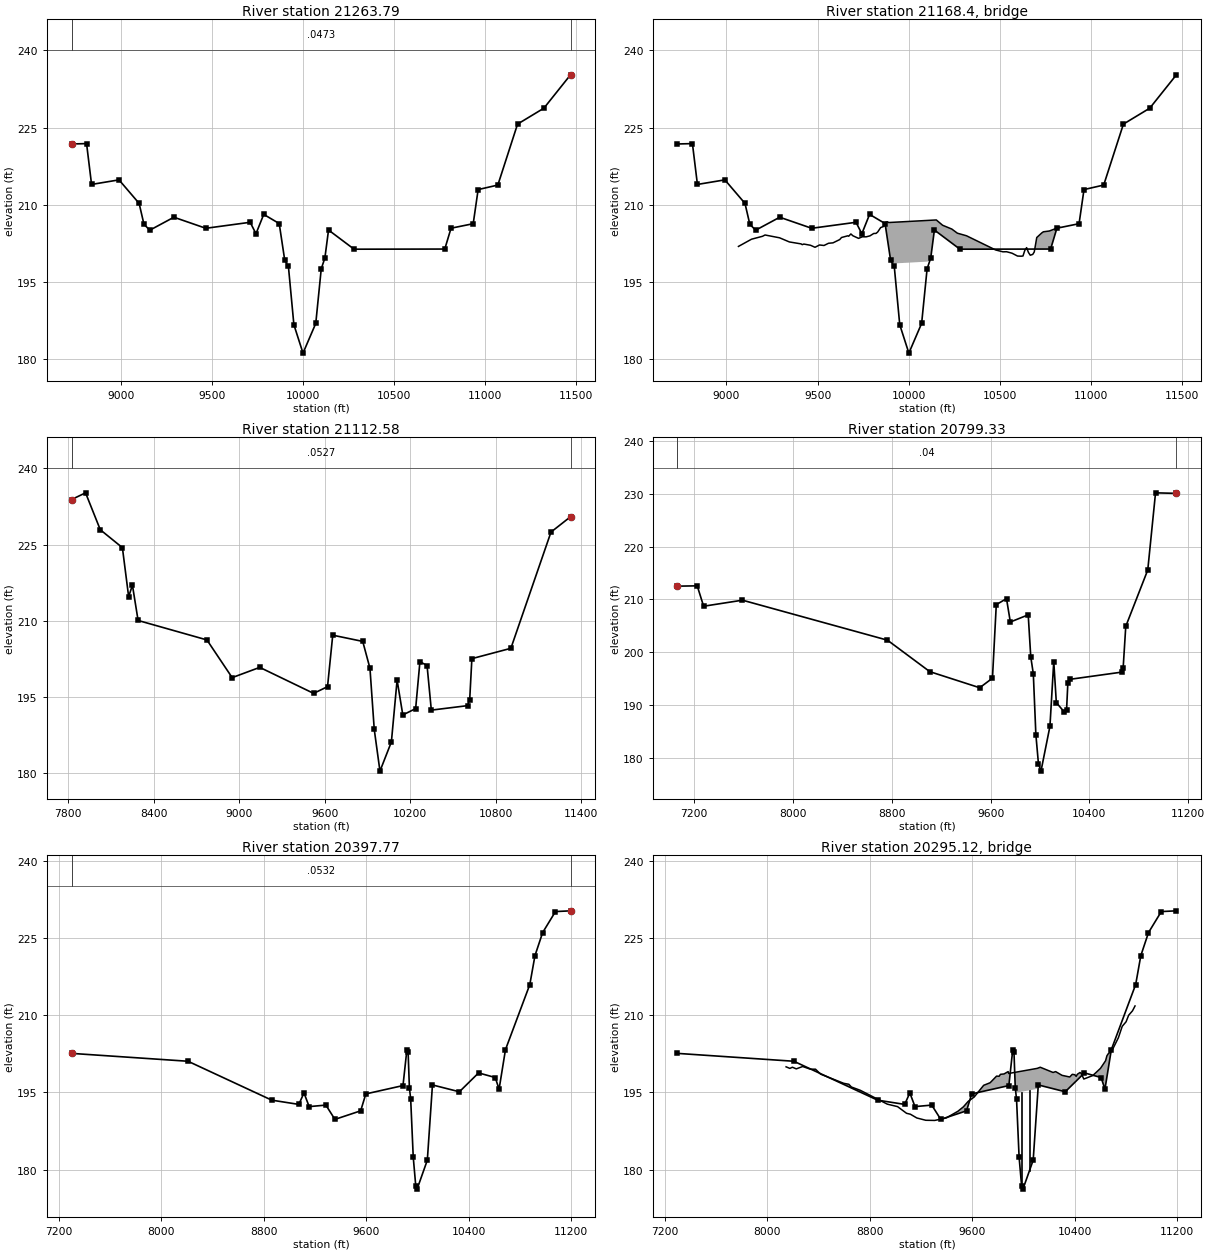
Type RM Length L Ch R = 1 ,21263.79,151.215500,151.215500,151.215500
XS GIS Cut Line= 6
792632.091373146804944.957367063793254.881777167804278.594216302
793334.123715788804057.756026715793288.657029688803317.298567533
793684.174706459802882.457367063793891.355947716 802725.15309129
#Sta/Elev= 30
8731.025221.83978813.092221.91438840.467213.9848 8991.03214.87239101.415210.3048
9127.906206.25489159.996205.10139292.157207.61759467.545205.47039710.679 206.635
9742.552 204.4099785.049208.17039870.043206.38889900.506199.23169920.515198.0549
9950.529186.746710000.55181.229310070.59187.0031 10100.6  197.5910120.61199.7052
10140.62205.132610280.68 201.41110778.41201.438510812.72205.484910934.38206.3618
10961.42212.987611069.56213.864611177.71225.702511322.22228.791811468.31 235.268
#Mann= 3 , 0 , 0
8731.025  0.0473       08731.025  0.0473       011468.31  0.0473       0
#XS Ineff= 2 , 0
       09841.349        10150.31       0
Bank Sta=8731.025,11468.31
Exp/Cntr=0.3,0.1

Type RM Length L Ch R = 3 , 21168.4,,,
BEGIN DESCRIPTION:
END DESCRIPTION:
Bridge Culvert--1,0,-1,-1, 0
Deck Dist Width WeirC Skew NumUp NumDn MinLoCord MaxHiCord MaxSubmerge Is_Ogee
39.607750,72.000000,2.6,0, 60, 60, , , 0.95, 0, 0,0,,
 9065.64 9137.26 9198.05 9211.39 9291.44 9344.81 9409.19 9415.68 9424.15 9461.09
 9485.72 9510.35 9534.98 9559.61 9584.24 9621.19 9631.06 9665.33 9670.45 9682.46
 9693.39 9724.59 9745.40 9766.20 9787.00 9807.80 9820.63 9829.55 9845.91 9862.21
 9873.10 9883.99 9889.24 9901.45 9901.4510115.4510115.4510151.2110185.6610236.34
10266.6510316.6510476.6510516.6610536.6610566.6610596.6610616.6610626.6610636.66
10646.6610656.6610666.6610680.1810688.5210702.2510729.7110738.5410770.9110828.09
  201.95  203.35  203.92  204.17  203.62  202.82  202.44  202.29  202.41  202.17
  201.78  202.23  202.13  202.56  202.64  203.28  203.68  204.01  203.93  204.37
  204.02  203.51  203.82  203.81  204.00  204.46  204.48  204.75  205.61  205.83
  206.63  206.73  206.59  206.61  206.61  207.02  207.02  207.09  206.06  205.32
  204.52  204.02  201.26  200.90  200.92  200.63  200.08  200.05  200.09  201.18
  201.71  200.78  200.24  200.40  200.87  203.68  204.57  204.79  204.94  205.71
 -798.05 -796.65 -796.08 -795.83 -796.38 -797.18 -797.56 -797.71 -797.59 -797.83
 -798.22 -797.77 -797.87 -797.44 -797.36 -796.72 -796.32 -795.99 -796.07 -795.63
 -795.98 -796.49 -796.18 -796.19 -796.00 -795.54 -795.52 -795.25 -794.39 -794.17
 -793.37 -793.27 -793.41 -793.39  198.61  199.02 -792.98 -792.91 -793.94 -794.68
 -795.48 -795.98 -798.74 -799.10 -799.08 -799.37 -799.92 -799.95 -799.91 -798.82
 -798.29 -799.22 -799.76 -799.60 -799.13 -796.32 -795.43 -795.21 -795.06 -794.29
 9065.64 9137.26 9198.05 9211.39 9291.44 9344.81 9409.19 9415.68 9424.15 9461.09
 9485.72 9510.35 9534.98 9559.61 9584.24 9621.19 9631.06 9665.33 9670.45 9682.46
 9693.39 9703.79 9724.59 9745.40 9766.20 9787.00 9807.80 9820.63 9829.55 9845.91
 9862.21 9873.10 9883.99 9913.39 9913.3910127.3910127.3910151.2110185.6610236.34
10266.6510316.6510466.6510516.6610536.6610566.6610596.6610616.6610626.6610636.66
10646.6610656.6610666.6610680.1810688.5210702.2510729.7110738.5410770.9110828.09
  201.95  203.35  203.92  204.17  203.62  202.82  202.44  202.29  202.41  202.17
  201.78  202.23  202.13  202.56  202.64  203.28  203.68  204.01  203.93  204.37
  204.02  203.95  203.51  203.82  203.81  204.00  204.46  204.48  204.75  205.61
  205.83  206.63  206.73  206.63  206.63  207.05  207.05  207.09  206.06  205.32
  204.52  204.02  201.40  200.90  200.92  200.63  200.08  200.05  200.09  201.18
  201.71  200.78  200.24  200.40  200.87  203.68  204.57  204.79  204.94  205.71
 -798.05 -796.65 -796.08 -795.83 -796.38 -797.18 -797.56 -797.71 -797.59 -797.83
 -798.22 -797.77 -797.87 -797.44 -797.36 -796.72 -796.32 -795.99 -796.07 -795.63
 -795.98 -796.05 -796.49 -796.18 -796.19 -796.00 -795.54 -795.52 -795.25 -794.39
 -794.17 -793.37 -793.27 -793.37  198.63  199.05 -792.95 -792.91 -793.94 -794.68
 -795.48 -795.98 -798.60 -799.10 -799.08 -799.37 -799.92 -799.95 -799.91 -798.82
 -798.29 -799.22 -799.76 -799.60 -799.13 -796.32 -795.43 -795.21 -795.06 -794.29
BR Coef=-1 , 0 , 0 ,, 0 ,,,0.8,0,1,0,
WSPro=,,,, 1 ,,,, 0 ,,,, 0 ,,,,-1 ,-1 ,-1 , 0 , 0 , 0 , 0 , 0
BC Design=,, 0 ,, 0 ,,,,,,

Type RM Length L Ch R = 1 ,21112.58,313.245300,313.245300,313.245300
XS GIS Cut Line= 6
792163.341373116805679.332367048792897.716373146805038.707367063
793397.777076334804322.761854231793457.533292323 804117.51224272
793462.729485005803442.007192224794038.341373116802939.749033719
#Sta/Elev= 30
7823.993233.86327921.857235.17988025.247227.90788180.463224.3816  8224.3214.7305
 8250.84216.99618290.651210.03798773.738 206.2048950.952198.77859144.581200.7985
9522.711195.67659620.293196.99999656.886207.13969867.372205.91389918.175200.6162
9948.247188.57439988.342180.361410068.53186.117310108.63198.299910148.72191.4288
10238.82192.675810268.84201.917810318.87 201.16710348.89192.3769 10603.1193.2585
10618.31194.465110633.52202.5168 10907.3204.5539 11188.8 227.44611325.95230.4694
#Mann= 3 , 0 , 0
7823.993  0.0527       07823.993  0.0527       011325.95  0.0527       0
#XS Ineff= 2 , 0
       09874.963        10151.36       0
Bank Sta=7823.993,11325.95
Exp/Cntr=0.3,0.1

Type RM Length L Ch R = 1 ,20799.33,401.557600,401.557600,401.557600
XS GIS Cut Line= 6
792439.383039773806648.082367048793376.542667083805516.252232315
793479.641946149805164.704465458793590.090106582804759.932093338
 793860.35812428803743.119041489794077.407487498803044.805551818
#Sta/Elev= 30
7065.328 212.5047225.126212.56637277.058208.71037591.573209.85268765.357  202.29
9108.146196.33889511.873193.29749615.242195.10319646.253209.00849728.948210.1473
9759.959205.72559904.675207.08359925.349199.13219946.023195.94579966.697184.4311
9987.371178.965510008.04177.5303 10080.5185.994210111.56198.255410132.26190.4977
10194.48188.766410215.24189.106910225.61194.2377 10240.5194.883610662.99 196.253
10673.46 197.11110694.41204.899210872.47215.5692 10935.4230.152111104.18230.0476
#Mann= 3 , 0 , 0
7065.328    0.04       07065.328    0.04       011104.18    0.04       0
#XS Ineff= 2 , 0
       09896.039        10173.16       0
Bank Sta=7065.328,11104.18
Exp/Cntr=0.3,0.1

Type RM Length L Ch R = 1 ,20397.77,192.495000,192.495000,192.495000
XS GIS Cut Line= 6
793416.098991245806612.610754609793986.258039773806023.082367063
794136.441113919804678.478012964794151.553558379804479.164274096
794169.133382976803820.155113056794180.945296973802957.243691847
#Sta/Elev= 30
7298.386 202.6158207.142201.08278861.105193.50699072.386192.68369112.629194.9224
9152.873192.25239283.666192.54559354.148189.76339555.297191.43199595.396194.7242
9885.672196.34739915.674203.23569925.675202.83969935.675195.91359945.676193.7357
9965.678182.42229985.679176.7142 9995.68176.184210075.69181.827910115.69196.4712
10325.85195.139510475.87198.813910605.88197.915110635.88195.640910685.89203.3508
10875.91216.027410915.91221.635910975.92226.133411075.93 230.22811193.69230.3735
#Mann= 3 , 0 , 0
7298.386  0.0532       07298.386  0.0532       011193.69  0.0532       0
#XS Ineff= 2 , 0
       09890.929        10169.04       0
Bank Sta=7298.386,11193.69
Exp/Cntr=0.3,0.1

Type RM Length L Ch R = 3 ,20295.12,,,
BEGIN DESCRIPTION:
END DESCRIPTION:
Bridge Culvert--1,0,-1,-1, 0
Deck Dist Width WeirC Skew NumUp NumDn MinLoCord MaxHiCord MaxSubmerge Is_Ogee
65.247500,62.000000,2.6,0, 60, 60, , , 0.95, 0, 0,0,,
 8146.37 8175.75 8195.77 8225.81 8275.87 8335.95 8376.00 8416.05 8596.27 8636.32
 8656.34 8726.43 8936.69 9016.79 9086.88 9116.92 9166.98 9237.07 9307.15 9397.26
 9487.62 9530.82 9568.19 9614.99 9689.04 9739.40 9789.76 9809.90 9819.97 9847.75
 9880.23 9884.38 9921.74 9921.7410107.7410107.7410130.7210230.9110250.9210300.92
10360.9310380.9310400.9410410.9410420.9410440.9410450.9410470.9410540.9510600.96
10640.9710650.9710660.9710690.9710740.9810770.9810800.9910820.9910850.9910870.81
  200.00  199.69  199.92  199.60  200.06  199.54  199.54  198.57  196.79  196.60
  196.07  195.42  192.73  192.25  190.95  190.77  190.04  189.59  189.56  190.05
  191.34  192.21  193.27  194.12  196.40  196.90  198.19  198.16  198.54  198.61
  199.07  198.70  198.87  198.87  199.70  199.70  199.92  198.90  199.07  198.34
  198.02  198.54  198.46  198.14  198.56  198.89  198.72  197.62  198.30  199.70
  201.19  202.13  202.52  203.17  205.67  207.89  208.77  210.04  210.90  211.85
 -800.00 -800.31 -800.08 -800.40 -799.94 -800.46 -800.46 -801.43 -803.21 -803.40
 -803.93 -804.58 -807.27 -807.75 -809.05 -809.23 -809.96 -810.41 -810.44 -809.95
 -808.66 -807.79 -806.73 -805.88 -803.60 -803.10 -801.81 -801.84 -801.46 -801.39
 -800.93 -801.30 -801.13  194.87  195.70 -800.30 -800.08 -801.10 -800.93 -801.66
 -801.98 -801.46 -801.54 -801.86 -801.44 -801.11 -801.28 -802.38 -801.70 -800.30
 -798.81 -797.87 -797.48 -796.83 -794.33 -792.11 -791.23 -789.96 -789.10 -788.15
 8146.37 8175.75 8195.77 8225.81 8275.87 8335.95 8376.00 8416.05 8596.27 8636.32
 8656.34 8726.43 8936.69 9016.79 9086.88 9116.92 9166.98 9237.07 9307.15 9397.26
 9487.62 9530.82 9568.19 9614.99 9689.04 9739.40 9789.76 9809.90 9819.97 9847.75
 9880.23 9884.38 9900.64 9900.6410086.6410086.6410130.7210230.9110250.9210300.92
10360.9310380.9310400.9410410.9410420.9410440.9410450.9410470.9410540.9510600.96
10640.9710650.9710660.9710690.9710740.9810770.9810800.9910820.9910850.9910870.81
  200.00  199.69  199.92  199.60  200.06  199.54  199.54  198.57  196.79  196.60
  196.07  195.42  192.73  192.25  190.95  190.77  190.04  189.59  189.56  190.05
  191.34  192.21  193.27  194.12  196.40  196.90  198.19  198.16  198.54  198.61
  199.07  198.70  198.78  198.78  199.61  199.61  199.92  198.90  199.07  198.34
  198.02  198.54  198.46  198.14  198.56  198.89  198.72  197.62  198.30  199.70
  201.19  202.13  202.52  203.17  205.67  207.89  208.77  210.04  210.90  211.85
 -800.00 -800.31 -800.08 -800.40 -799.94 -800.46 -800.46 -801.43 -803.21 -803.40
 -803.93 -804.58 -807.27 -807.75 -809.05 -809.23 -809.96 -810.41 -810.44 -809.95
 -808.66 -807.79 -806.73 -805.88 -803.60 -803.10 -801.81 -801.84 -801.46 -801.39
 -800.93 -801.30 -801.22  194.78  195.61 -800.39 -800.08 -801.10 -800.93 -801.66
 -801.98 -801.46 -801.54 -801.86 -801.44 -801.11 -801.28 -802.38 -801.70 -800.30
 -798.81 -797.87 -797.48 -796.83 -794.33 -792.11 -791.23 -789.96 -789.10 -788.15
Pier Skew, UpSta & Num, DnSta & Num=  ,9983.07, 2 ,9961.97, 2 , 0 , 0 , 0 ,,
    4.00    4.00
 -800.86  199.14
    4.00    4.00
 -800.95  199.05
Pier Skew, UpSta & Num, DnSta & Num=  ,10046.40, 2 ,10025.31, 2 , 0 , 0 , 0 ,,
    4.00    4.00
 -800.57  199.43
    4.00    4.00
 -800.67  199.33
BR Coef=-1 , 0 , 0 ,, 0 ,,,0.8,0,1,0,
WSPro=,,,, 1 ,,,, 0 ,,,, 0 ,,,,-1 ,-1 ,-1 , 0 , 0 , 0 , 0 , 0
BC Design=,, 0 ,, 0 ,,,,,,

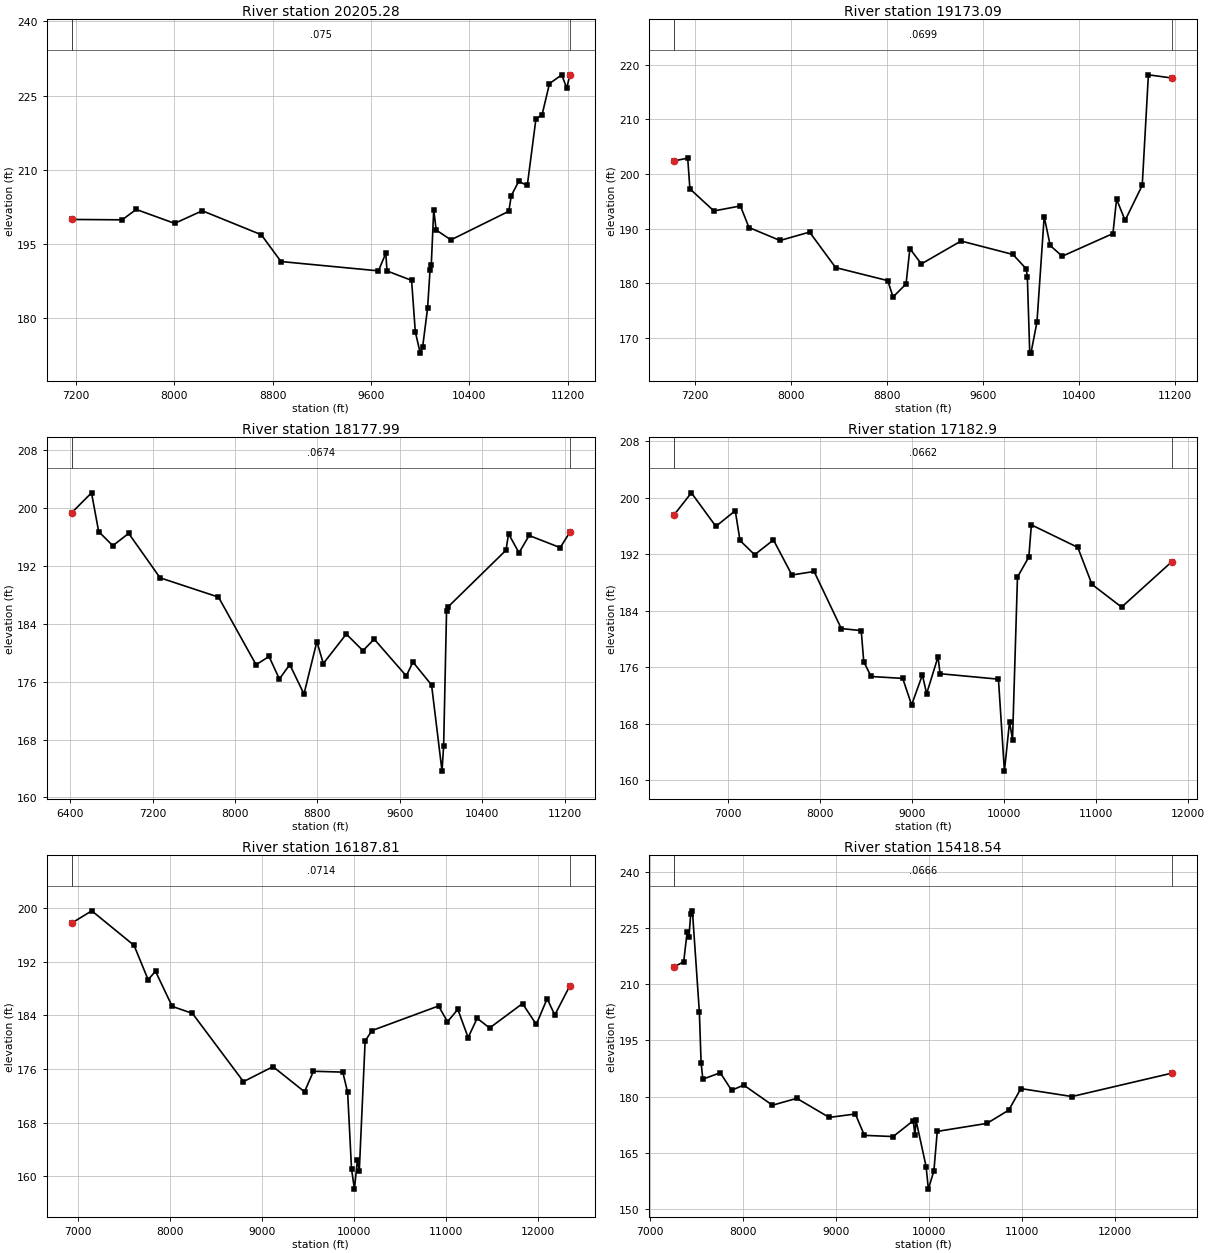
Type RM Length L Ch R = 1 ,20205.28,1032.191400,1032.191400,1032.191400
XS GIS Cut Line= 6
793659.154546827806751.499643505794259.009854674806029.367196083
794292.104970634805058.690855771794345.038148582804510.832464173
794356.012892425803858.004903018794416.497938782802920.190467283
#Sta/Elev= 30
7163.527 199.9777574.978199.90227689.127 202.0018002.128199.18028226.743201.7337
8707.022196.88688867.115191.46749659.791189.58519719.799193.12969729.801189.5633
9929.829187.66039959.833177.29589999.839172.953810019.84174.230210059.85182.0441
10079.85189.753810089.85190.794210109.85 201.91510129.86197.835110249.87195.8488
 10720.8201.634610740.84204.787310800.96 207.66110871.11206.859910941.26220.2922
10991.36221.145611051.48227.438611151.69229.213611191.77226.507711216.64229.1228
#Mann= 3 , 0 , 0
7163.527   0.075       07163.527   0.075       011216.64   0.075       0
#XS Ineff= 2 , 0
       09863.099        10164.45       0
Bank Sta=7163.527,11216.64
Exp/Cntr=0.3,0.1

Type RM Length L Ch R = 1 ,19173.09,995.092500,995.092500,995.092500
XS GIS Cut Line= 6
794191.138129739806888.820618165794894.770298689805786.867152843
795208.124533282805132.873650167795307.813162308804735.847917491
795395.368832199803635.713279481795515.833254325803044.298818005
#Sta/Elev= 30
7023.961202.38177140.137202.90167158.329197.27167358.438193.21857579.108194.1369
7650.645190.1826 7909.44187.80368155.633189.34518372.818182.83948807.281180.4461
8851.194177.44668959.483179.82938991.537186.30579087.152183.50799417.786187.7084
9850.096185.24539960.298182.63259970.323181.19399990.374167.1953 10000.4167.1587
10050.54172.860510110.71192.186110160.81186.888710261.01184.918110683.63189.0754
10713.97195.390410785.08191.487910927.81197.918110979.17 218.17111175.65217.5875
#Mann= 3 , 0 , 0
7023.961  0.0699       07023.961  0.0699       011175.65  0.0699       0
#XS Ineff= 2 , 0
       09360.391         10168.1       0
Bank Sta=7023.961,11175.65
Exp/Cntr=0.3,0.1

Type RM Length L Ch R = 1 ,18177.99,995.092400,995.092400,995.092400
XS GIS Cut Line= 6
794123.642615037807206.358953492794698.770582884 806408.69764869
795580.824455615805242.754731856796015.283401012 804644.09859333
796525.125691588804066.748714676797059.611368515803369.936636385
#Sta/Elev= 30
6414.705199.35046608.257202.11696677.499 196.7616814.843 194.8096968.844196.5099
7273.279190.36847840.285187.6991 8204.89178.35048330.616179.49268431.196176.3751
8531.777178.37668669.797174.30018794.812181.5519 8857.32 178.5169080.336182.5931
9242.127 180.2949350.924181.89289662.482176.80339727.099178.72489907.784175.5487
10009.25163.642810024.91167.163210053.12185.786210066.02186.322710629.54194.1757
10655.03196.448410756.06193.823510854.29196.2205 11155.8194.541311248.76196.6424
#Mann= 3 , 0 , 0
6414.705  0.0674       06414.705  0.0674       011248.76  0.0674       0
#XS Ineff= 2 , 0
       08891.237        10168.87       0
Bank Sta=6414.705,11248.76
Exp/Cntr=0.3,0.1

Type RM Length L Ch R = 1 , 17182.9,995.092500,995.092500,995.092500
XS GIS Cut Line= 6
794072.027361527807509.319815707794923.091815289806431.902675636
795614.719107877805758.575844576796134.189978222805441.663535822
 797410.47454628804893.381012587798255.647343802804232.109808746
#Sta/Elev= 30
6406.162197.49996597.437200.67056863.743195.92997074.754198.14167125.928193.9364
7285.031191.91537489.864194.00617690.673189.04937931.814189.5475 8227.29181.4761
8444.225181.18518471.595176.79028551.551174.69768895.461174.42548991.904170.6773
9109.201174.92059155.322172.25639279.151177.4779 9301.41175.09029936.076174.3195
   10001161.3142 10056.7168.297110089.17165.756310142.97188.750410266.45191.5966
10294.01196.140210798.69192.955110952.63187.725211274.97184.507611822.76190.9512
#Mann= 3 , 0 , 0
6406.162  0.0662       06406.162  0.0662       011822.76  0.0662       0
#XS Ineff= 2 , 0
       0 8961.69        10212.59       0
Bank Sta=6406.162,11822.76
Exp/Cntr=0.3,0.1

Type RM Length L Ch R = 1 ,16187.81,769.269300,769.269300,769.269300
XS GIS Cut Line= 6
794445.962210617807877.754037865795650.709726278806772.418176332
796314.637063635806395.028686322797618.466396514805851.639317786
798245.156057392805382.504171062798826.382304898804805.773372863
#Sta/Elev= 30
6926.734197.71617146.318199.55557606.735194.41027759.555189.30527840.316190.5468
8021.866185.31768241.877184.27838797.507174.11039118.948 176.3449461.863172.5992
9559.126175.65729878.292175.52789931.184172.51779973.497 161.10610005.23158.0975
10036.98162.416410058.15160.831910121.66180.177710195.99181.717910920.22185.3798
11018.02183.036411130.53184.874811242.73180.6709 11340.6 183.54911476.53182.1053
11834.48  185.7411984.46182.631312102.57  186.4712185.76184.0369 12348.8188.3671
#Mann= 3 , 0 , 0
6926.734  0.0714       06926.734  0.0714       0 12348.8  0.0714       0
#XS Ineff= 2 , 0
       08964.132         10283.6       0
Bank Sta=6926.734,12348.8
Exp/Cntr=0.3,0.1

Type RM Length L Ch R = 1 ,15418.54,201.239100,201.239100,201.239100
XS GIS Cut Line= 6
795069.591373146808122.040700376796237.010759294807383.550024405
796900.739391804807112.024674758797614.032175392806603.453384921
 798391.97385174805954.809494078799102.522851348804786.443138212
#Sta/Elev= 30
7258.272214.57437364.969216.00437402.381224.05037421.086222.48277439.792228.6328
7458.497229.5926 7533.32202.56617552.025188.99917570.731184.64397757.787186.3585
7879.979181.67028010.141183.06928318.954177.69248580.832179.52528929.208174.4318
9210.123175.35149307.363169.6466 9616.59169.32129832.085173.54929850.579169.8413
9862.574173.63349970.529161.32479995.056155.287110054.49160.197410090.48   170.7
10625.12172.843110859.48176.392810989.68182.125611538.52180.008712613.61186.2578
#Mann= 3 , 0 , 0
7258.272  0.0666       07258.272  0.0666       012613.61  0.0666       0
#XS Ineff= 2 , 0
       09223.927        10310.75       0
Bank Sta=7258.272,12613.61
Exp/Cntr=0.3,0.1

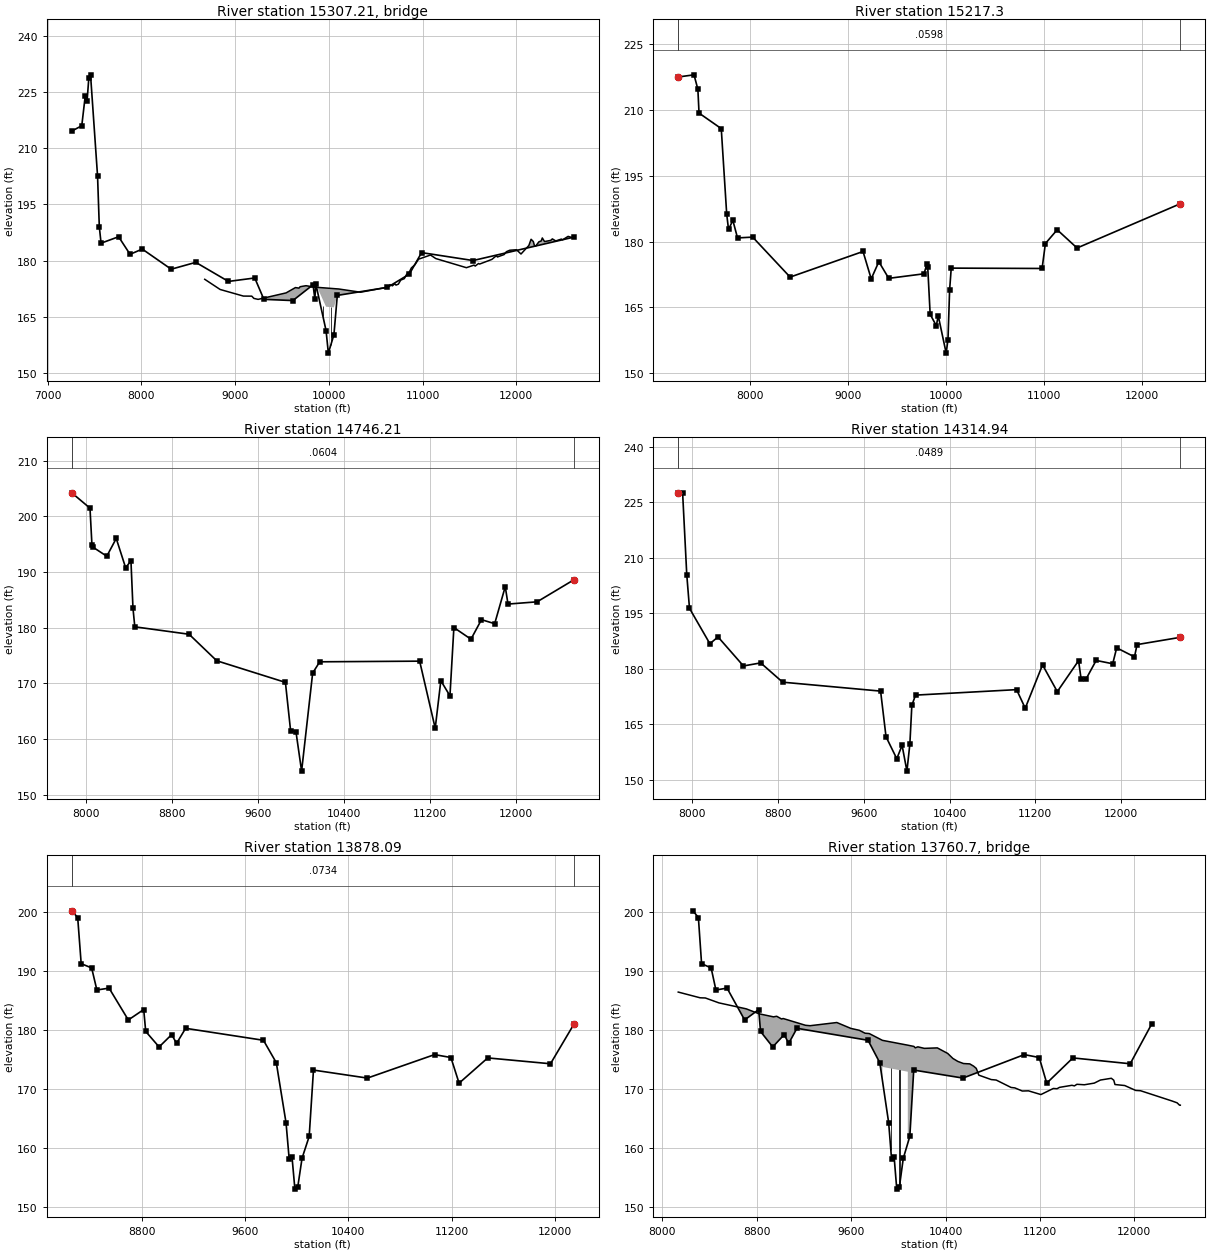
Type RM Length L Ch R = 3 ,15307.21,,,
BEGIN DESCRIPTION:
END DESCRIPTION:
Bridge Culvert--1,0,-1,-1, 0
Deck Dist Width WeirC Skew NumUp NumDn MinLoCord MaxHiCord MaxSubmerge Is_Ogee
66.619550,68.000000,2.6,0, 60, 60, , , 0.95, 0, 0,0,,
 8676.51 8840.88 9088.65 9178.27 9200.67 9245.48 9544.22 9644.09 9681.54 9694.03
 9756.45 9852.19 9852.1910107.1910107.1910338.1210627.7710653.0910678.4210703.74
10716.4010741.7310767.0510805.0410830.3610855.6910880.2810919.0010956.9911084.72
11140.6111467.5411549.3411561.2111596.8311608.7111739.3211786.8111798.6811870.23
11894.1711930.0812002.1512049.7712133.5612157.4912181.4312193.4012205.3712241.28
12265.2212277.1912301.1312366.1012384.2912420.6912480.6612492.6312552.4812594.52
  175.00  172.28  170.52  170.50  169.90  169.64  171.37  172.79  172.64  173.02
  173.29  172.90  172.90  172.41  172.41  171.55  172.89  173.57  173.26  173.82
  173.45  173.70  174.79  175.17  176.34  176.76  178.03  178.90  180.37  181.48
  180.54  178.10  178.79  178.53  179.21  179.07  180.31  181.29  180.96  181.61
  182.37  182.76  182.89  181.75  184.02  185.69  185.08  183.98  183.84  185.02
  185.23  186.04  185.08  185.38  185.79  185.24  185.74  185.53  186.46  186.15
 -825.00 -827.72 -829.48 -829.50 -830.10 -830.36 -828.63 -827.21 -827.36 -826.98
 -826.71 -827.10  167.90  167.41 -827.59 -828.45 -827.11 -826.43 -826.74 -826.18
 -826.55 -826.30 -825.21 -824.83 -823.66 -823.24 -821.97 -821.10 -819.63 -818.52
 -819.46 -821.90 -821.21 -821.47 -820.79 -820.93 -819.69 -818.71 -819.04 -818.39
 -817.63 -817.24 -817.11 -818.25 -815.98 -814.31 -814.92 -816.02 -816.16 -814.98
 -814.77 -813.96 -814.92 -814.62 -814.21 -814.76 -814.26 -814.47 -813.54 -813.85
 8676.51 8840.88 9088.65 9178.27 9200.67 9245.48 9544.22 9644.09 9681.54 9694.03
 9756.45 9785.03 9785.0310040.0310040.0310338.1210627.7710653.0910678.4210703.74
10716.4010741.7310767.0510805.0410830.3610855.6910880.2810919.0010956.9911084.72
11140.6111467.5411549.3411561.2111596.8311608.7111739.3211786.8111798.6811870.23
11894.1711930.0812002.1512049.7712133.5612157.4912181.4312193.4012205.3712241.28
12265.2212277.1912301.1312366.1012384.2912420.6912480.6612492.6312552.4812594.52
  175.00  172.28  170.52  170.50  169.90  169.64  171.37  172.79  172.64  173.02
  173.29  173.03  173.03  172.54  172.54  171.55  172.89  173.57  173.26  173.82
  173.45  173.70  174.79  175.17  176.34  176.76  178.03  178.90  180.37  181.48
  180.54  178.10  178.79  178.53  179.21  179.07  180.31  181.29  180.96  181.61
  182.37  182.76  182.89  181.75  184.02  185.69  185.08  183.98  183.84  185.02
  185.23  186.04  185.08  185.38  185.79  185.24  185.74  185.53  186.46  186.15
 -825.00 -827.72 -829.48 -829.50 -830.10 -830.36 -828.63 -827.21 -827.36 -826.98
 -826.71 -826.97  168.03  167.54 -827.46 -828.45 -827.11 -826.43 -826.74 -826.18
 -826.55 -826.30 -825.21 -824.83 -823.66 -823.24 -821.97 -821.10 -819.63 -818.52
 -819.46 -821.90 -821.21 -821.47 -820.79 -820.93 -819.69 -818.71 -819.04 -818.39
 -817.63 -817.24 -817.11 -818.25 -815.98 -814.31 -814.92 -816.02 -816.16 -814.98
 -814.77 -813.96 -814.92 -814.62 -814.21 -814.76 -814.26 -814.47 -813.54 -813.85
Pier Skew, UpSta & Num, DnSta & Num=  ,9936.52, 2 ,9869.36, 2 , 0 , 0 , 0 ,,
    4.00    4.00
 -827.26  172.74
    4.00    4.00
 -827.13  172.87
Pier Skew, UpSta & Num, DnSta & Num=  ,10022.86, 2 ,9955.69, 2 , 0 , 0 , 0 ,,
    4.00    4.00
 -827.43  172.57
    4.00    4.00
 -827.30  172.70
BR Coef=-1 , 0 , 0 ,, 0 ,,,0.8,0,1,0,
WSPro=,,,, 1 ,,,, 0 ,,,, 0 ,,,,-1 ,-1 ,-1 , 0 , 0 , 0 , 0 , 0
BC Design=,, 0 ,, 0 ,,,,,,

Type RM Length L Ch R = 1 , 15217.3,471.087000,471.087000,471.087000
XS GIS Cut Line= 6
795246.674706489808241.832367063796090.424706459807700.165700391
796840.400425166807351.225577995  797663.5963265806786.625247777
798519.116674244806071.177501082799216.936215788805129.683231473
#Sta/Elev= 30
7272.057217.54137432.788218.03187472.083214.74827483.966209.30917710.446205.7742
7765.978186.25547784.489182.79397828.582184.85277876.116180.85788030.599181.0395
8412.111171.92799154.994177.76499238.342171.52329316.001175.43099416.947171.6445
9776.353172.68039805.296174.84189813.986174.29059839.074163.45679901.796160.8261
9921.239 163.12910002.15154.597410020.62 157.67710037.18 168.94710053.74173.9753
10979.57173.892111013.15179.577111133.31182.715111335.77 178.55912387.96188.6486
#Mann= 3 , 0 , 0
7272.057  0.0598       07272.057  0.0598       012387.96  0.0598       0
#XS Ineff= 2 , 0
       09262.658        10293.09       0
Bank Sta=7272.057,12387.96
Exp/Cntr=0.3,0.1

Type RM Length L Ch R = 1 ,14746.21,431.276100,431.276100,431.276100
XS GIS Cut Line= 6
796107.346802355808489.437131363796684.135960797808054.571465372
797773.772762203 807279.97640757798096.485170156807004.784191414
798460.523322596 806577.81764222799406.130611199805259.972531055
#Sta/Elev= 30
7868.726204.23018038.171201.4719 8056.04194.9265  8068.6194.42438194.202192.8363
8282.123 196.0268369.353190.76868418.878192.00668437.783183.47488454.743180.1436
8959.423 178.809 9216.45174.04289854.834170.15929902.981161.47769952.734161.3138
10005.34 154.20510108.13171.834910173.95173.8566 11102.8173.973111247.45161.9153
11299.71170.4606 11384.4167.738711421.03180.0129 11579.8177.919311677.49 181.432
11800.22180.707811898.61187.368311923.92184.233412194.55184.637812536.21188.5921
#Mann= 3 , 0 , 0
7868.726  0.0604       07868.726  0.0604       012536.21  0.0604       0
#XS Ineff= 2 , 0
       09535.987        10395.08       0
Bank Sta=7868.726,12536.21
Exp/Cntr=0.3,0.1

Type RM Length L Ch R = 1 ,14314.94,436.846700,436.846700,436.846700
XS GIS Cut Line= 6
796443.005927412808757.528510469797940.727448436 807704.23595375
798144.895466832807529.084269419798525.030958348 807058.79812227
799153.443836074806000.202998706799568.120921483805382.929031656
#Sta/Elev= 30
7869.567227.50477910.679 227.3487949.074205.41637974.428196.34448164.583186.7933
8240.645188.62338477.635180.78988638.411181.61648843.086176.41389756.555174.0046
9807.252161.67779907.526155.7562 9956.99159.372310002.09152.412910029.56159.7419
10047.99170.173510082.41172.922711024.67174.400611105.34169.384511266.67181.0795
11404.27173.865611602.64182.210511625.98177.351111672.64177.275611766.74182.2805
11921.02181.379611958.14185.679812124.07183.235112148.21186.554512551.44188.5154
#Mann= 3 , 0 , 0
7869.567  0.0489       07869.567  0.0489       012551.44  0.0489       0
#XS Ineff= 2 , 0
       0 9644.68        10201.03       0
Bank Sta=7869.567,12551.44
Exp/Cntr=0.3,0.1

Type RM Length L Ch R = 1 ,13878.09,302.376500,302.376500,302.376500
XS GIS Cut Line= 6
796981.049706489808928.937796339797537.394403428808424.518604413
798060.358418614808020.241457969798652.106239945807740.640748143
799228.682282239807489.859513506 800356.20753476807107.836154938
#Sta/Elev= 30
8259.803200.17038305.631199.03398332.627191.21178413.617190.49368454.112186.7524
8548.535 187.0718697.413181.67278816.516183.43728832.065179.72928935.619177.1014
9033.028179.19329070.947 177.7029140.791180.25839743.277178.22899842.818174.4226
9918.128164.24099942.359 158.1159964.479158.41499986.599153.002110008.72153.3592
 10041.9158.2293 10097.2 161.93810130.38173.179210547.52171.823311067.27175.8006
11193.97  175.3111257.32170.961211479.05 175.24111964.73174.2499 12145.5180.9417
#Mann= 3 , 0 , 0
8259.803  0.0734       08259.803  0.0734       0 12145.5  0.0734       0
#XS Ineff= 2 , 0
       09829.372        10120.03       0
Bank Sta=8259.803,12145.5
Exp/Cntr=0.3,0.1

Type RM Length L Ch R = 3 , 13760.7,,,
BEGIN DESCRIPTION:
END DESCRIPTION:
Bridge Culvert--1,0,-1,-1, 0
Deck Dist Width WeirC Skew NumUp NumDn MinLoCord MaxHiCord MaxSubmerge Is_Ogee
96.188250,110.000000,2.6,0, 60, 60, , , 0.95, 0, 0,0,,
 8134.86 8320.29 8364.52 8479.42 8710.77 8819.64 8942.13 8968.99 9010.17 9023.78
 9213.38 9251.74 9478.60 9598.09 9669.79 9717.58 9753.43 9865.09 9865.0910080.09
10080.0910131.8410143.3110165.3510220.3310330.2910418.2510462.2410503.8510551.94
10605.1810638.1710660.1610681.9210787.1310829.2110955.4610987.0211050.1411102.75
11207.9511313.1611344.7211365.7611470.9711492.0111513.0511576.1811660.2511712.21
11804.7311825.3711835.6911918.2512011.1412052.4212319.0312362.0312382.6712389.31
  186.40  185.43  185.40  184.57  183.56  182.72  182.20  182.30  181.84  181.92
  180.77  180.70  181.24  180.24  179.92  179.43  179.37  178.22  178.22  177.40
  177.40  177.19  176.95  177.12  176.86  176.94  176.00  175.15  174.65  174.29
  174.23  173.84  173.47  172.32  171.57  171.49  170.23  170.16  169.63  169.66
  169.03  170.06  170.02  170.25  170.60  170.50  170.77  170.69  170.97  171.49
  171.79  171.46  170.73  170.56  169.73  169.68  167.94  167.63  167.23  167.23
 -813.60 -814.57 -814.60 -815.43 -816.44 -817.28 -817.80 -817.70 -818.16 -818.08
 -819.23 -819.30 -818.76 -819.76 -820.08 -820.57 -820.63 -821.78  173.72  172.90
 -822.60 -822.81 -823.05 -822.88 -823.14 -823.06 -824.00 -824.85 -825.35 -825.71
 -825.77 -826.16 -826.53 -827.68 -828.43 -828.51 -829.77 -829.84 -830.37 -830.34
 -830.97 -829.94 -829.98 -829.75 -829.40 -829.50 -829.23 -829.31 -829.03 -828.51
 -828.21 -828.54 -829.27 -829.44 -830.27 -830.32 -832.06 -832.37 -832.77 -832.77
 8134.86 8320.29 8364.52 8479.42 8710.77 8819.64 8942.13 8968.99 9010.17 9023.78
 9213.38 9251.74 9478.60 9598.09 9669.79 9717.58 9753.43 9799.35 9856.67 9938.43
 9938.4310153.4310153.4310220.3310330.2910418.2510462.2410503.8510551.9410605.18
10638.1710660.1610681.9210787.1310829.2110955.4610987.0211008.0611050.1411102.75
11207.9511313.1611344.7211365.7611470.9711492.0111513.0511576.1811660.2511712.21
11804.7311825.3711835.6911918.2512011.1412052.4212319.0312362.0312382.6712389.31
  186.40  185.43  185.40  184.57  183.56  182.72  182.20  182.30  181.84  181.92
  180.77  180.70  181.24  180.24  179.92  179.43  179.37  178.98  178.19  177.94
  177.94  177.03  177.03  176.86  176.94  176.00  175.15  174.65  174.29  174.23
  173.84  173.47  172.32  171.57  171.49  170.23  170.16  169.83  169.63  169.66
  169.03  170.06  170.02  170.25  170.60  170.50  170.77  170.69  170.97  171.49
  171.79  171.46  170.73  170.56  169.73  169.68  167.94  167.63  167.23  167.23
 -813.60 -814.57 -814.60 -815.43 -816.44 -817.28 -817.80 -817.70 -818.16 -818.08
 -819.23 -819.30 -818.76 -819.76 -820.08 -820.57 -820.63 -821.02 -821.81 -822.06
  173.44  172.53 -822.97 -823.14 -823.06 -824.00 -824.85 -825.35 -825.71 -825.77
 -826.16 -826.53 -827.68 -828.43 -828.51 -829.77 -829.84 -830.17 -830.37 -830.34
 -830.97 -829.94 -829.98 -829.75 -829.40 -829.50 -829.23 -829.31 -829.03 -828.51
 -828.21 -828.54 -829.27 -829.44 -830.27 -830.32 -832.06 -832.37 -832.77 -832.77
Pier Skew, UpSta & Num, DnSta & Num=  ,9936.09, 2 ,10009.43, 2 , 0 , 0 , 0 ,,
    4.00    4.00
 -822.05  177.95
    4.00    4.00
 -822.33  177.67
Pier Skew, UpSta & Num, DnSta & Num=  ,10009.09, 2 ,10082.43, 2 , 0 , 0 , 0 ,,
    4.00    4.00
 -822.33  177.67
    4.00    4.00
 -822.60  177.40
BR Coef=-1 , 0 , 0 ,, 0 ,,,0.8,0,1,0,
WSPro=,,,, 1 ,,,, 0 ,,,, 0 ,,,,-1 ,-1 ,-1 , 0 , 0 , 0 , 0 , 0
BC Design=,, 0 ,, 0 ,,,,,,