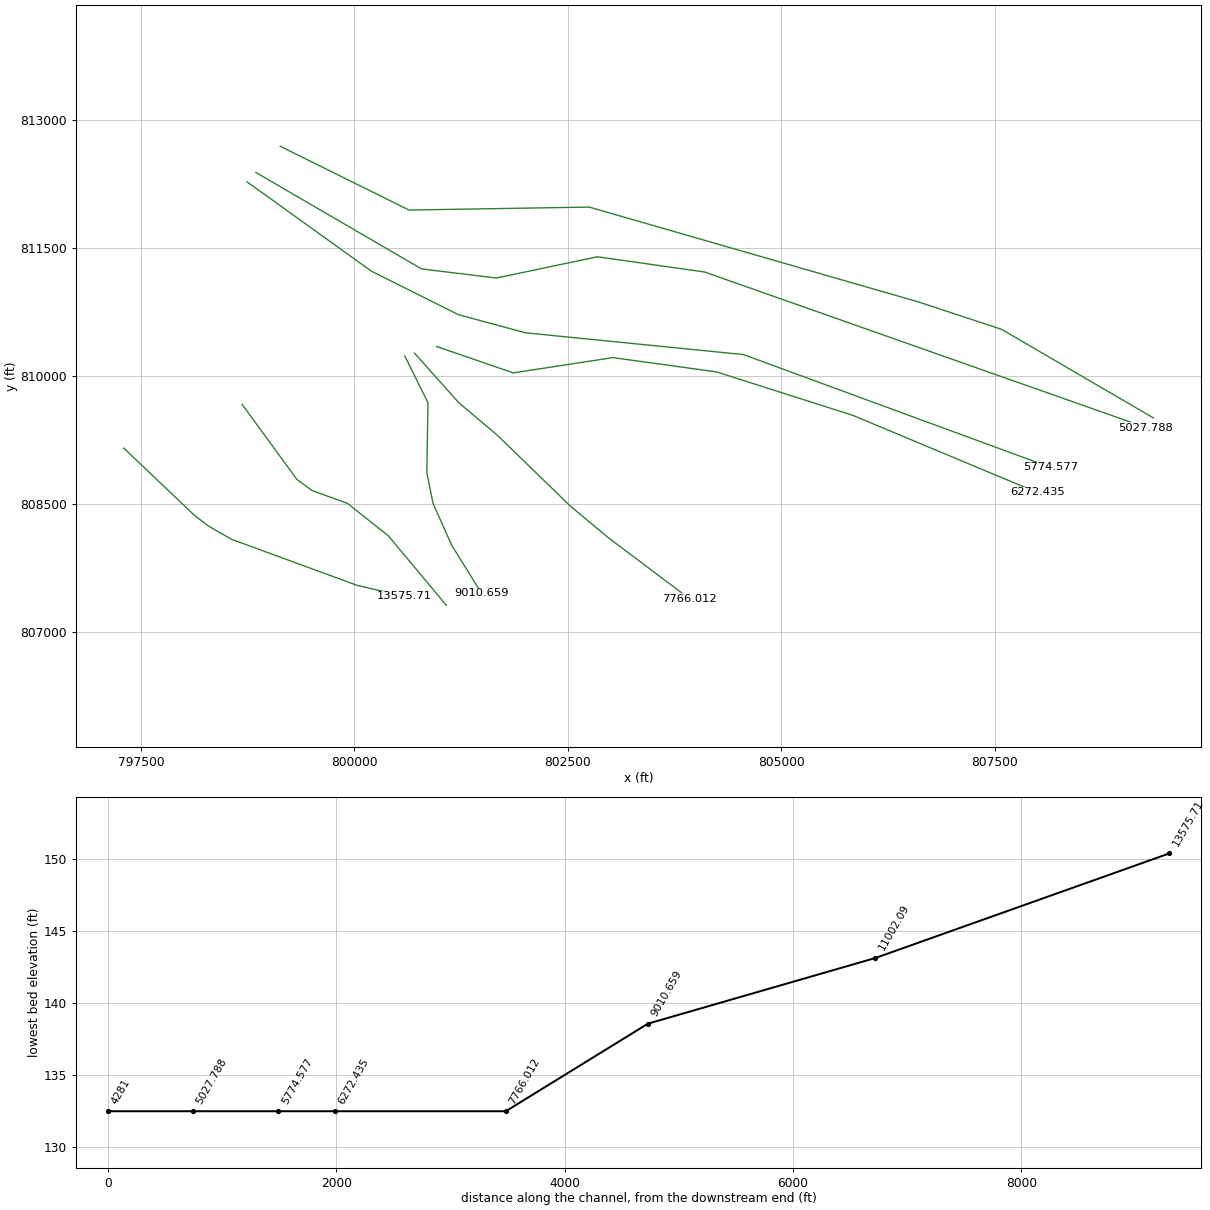
HEC-RAS study 17646_ras.prj: 17646

--- 17646_ras.g01 (geometry) --- (continued)

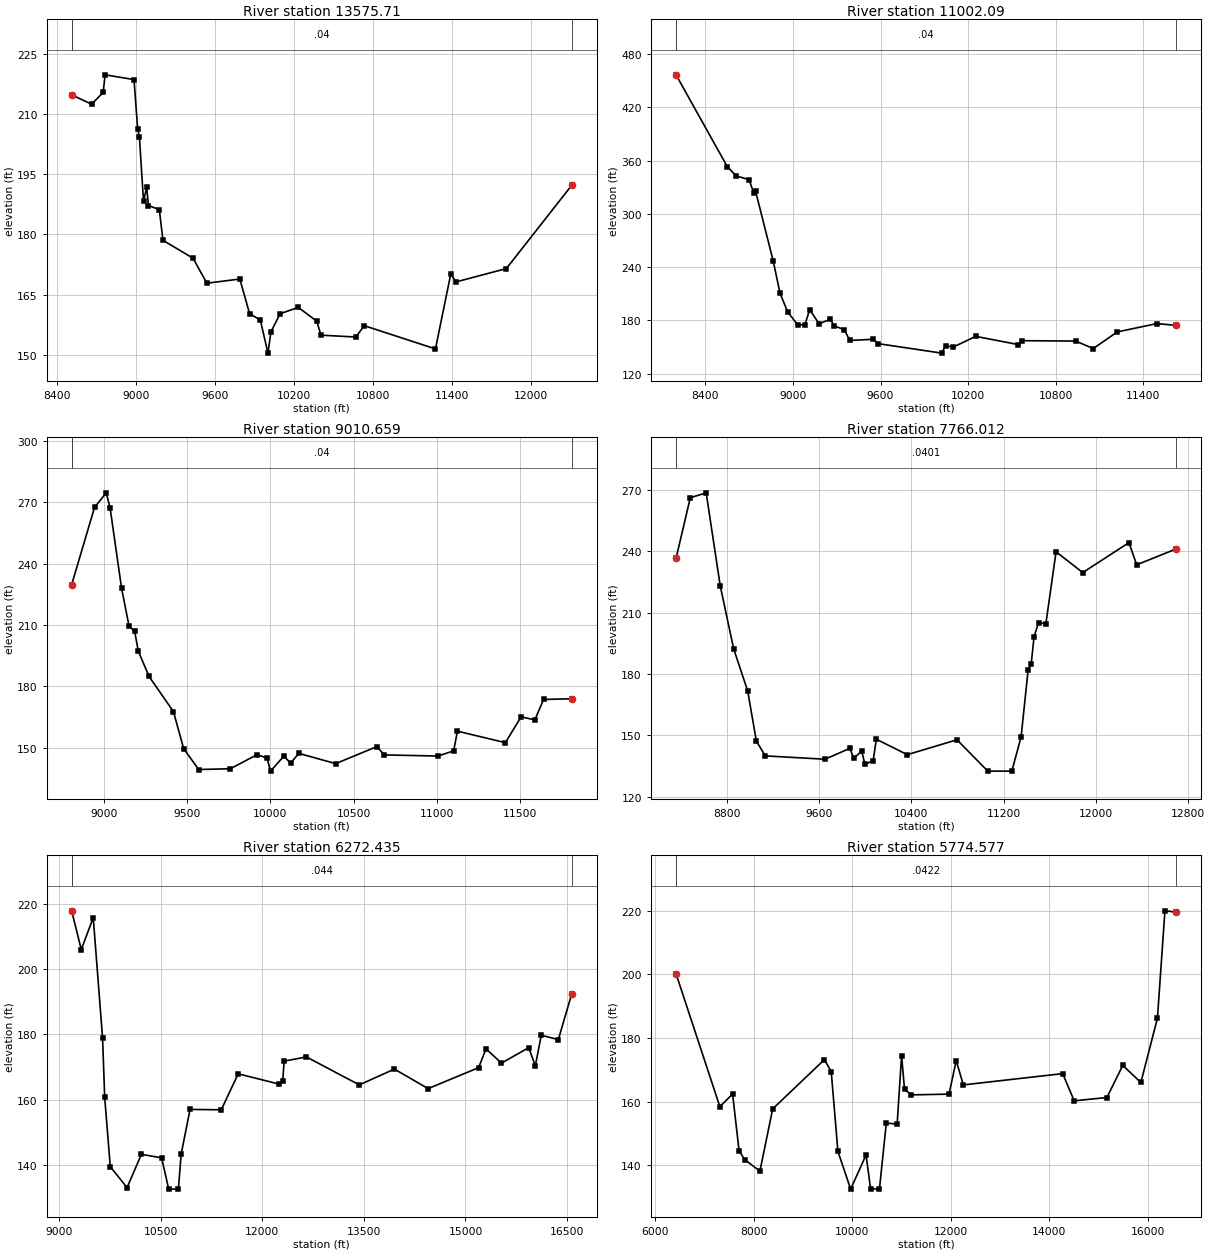
Type RM Length L Ch R = 1 ,13575.71,2573.619800,2573.619800,2573.619800
XS GIS Cut Line= 6
797300.020666033809158.893604428 798125.00000003808374.449903369
798288.057723671808248.485436216798560.031173229 808092.16424793
 800035.00000003807551.029151693800589.872307479807423.098149896
#Sta/Elev= 30
8512.232214.75818663.896212.41378751.484215.36758766.144219.73988985.767218.5544
 9013.22206.35729026.947204.14769058.042188.20189081.852191.71289095.579187.1584
9177.938186.18039205.537178.50829434.066174.04759539.374167.81419789.653168.8609
9863.694160.23199945.445158.641710003.12150.394610026.18155.695410095.39160.2112
10233.99161.7875 10374.2158.339710406.01154.870810671.16154.405910734.79157.2347
11275.69151.443211392.35170.174111430.25168.126111814.18171.460812311.77192.2504
#Mann= 3 , 0 , 0
8512.232    0.04       08512.232    0.04       012311.77    0.04       0
#XS Ineff= 2 , 0
       09934.295        10170.31       0
Bank Sta=8512.232,12311.77
Exp/Cntr=0.3,0.1

Type RM Length L Ch R = 1 ,11002.09,1991.435300,1991.435300,1991.435300
XS GIS Cut Line= 6
798686.704887058809670.996738091799328.134734659808792.217202238
 799507.54535327808661.358294009799919.047555486808512.168531134
800398.339696796808132.380319134 801078.89116957807316.906702894
#Sta/Elev= 30
8198.422 456.6598549.536353.27868610.198342.82088699.009338.5567 8731.52323.3185
8743.653325.53548864.975246.60918910.937210.81368962.553189.76449031.728175.1796
9081.356174.87799114.441192.18679178.541176.24259255.791181.21859282.803173.7087
9350.843169.74039389.581157.41359551.424158.72659583.367153.818310019.59143.1282
10045.59151.550810097.59149.859810252.53162.007910541.58152.835710572.75157.1603
10937.72 156.70111058.36148.243411222.72167.0354 11494.8176.389511626.97174.4202
#Mann= 3 , 0 , 0
8198.422    0.04       08198.422    0.04       011626.97    0.04       0
#XS Ineff= 2 , 0
       0                10240.08       0
Bank Sta=8198.422,11626.97
Exp/Cntr=0.3,0.1

Type RM Length L Ch R = 1 ,9010.659,1244.647100,1244.647100,1244.647100
XS GIS Cut Line= 6
800591.099001426810238.900133952800862.695823465809690.825125548
800849.544264024808871.656646465800922.023376961808511.677058471
801141.546283911808020.156291719801489.493426677807460.140048408
#Sta/Elev= 30
 8806.25229.74048943.685267.54499014.243274.62479037.422 267.0699106.041227.9568
9151.191209.38059184.246207.08619206.229197.32979271.166184.84329417.742167.6833
9478.841149.61049569.375139.35399759.558139.72739920.212 146.6199980.666144.9255
10000.86 138.56510081.22145.910810121.28142.476710171.29147.2434 10392.5142.2274
10641.19150.588910683.61146.491111006.77145.944711101.42148.460311123.93158.1058
11412.17152.471811506.47165.119311589.25163.616211641.51173.605611811.46 173.936
#Mann= 3 , 0 , 0
 8806.25    0.04       0 8806.25    0.04       011811.46    0.04       0
#XS Ineff= 2 , 0
       0                10437.12       0
Bank Sta=8806.25,11811.46
Exp/Cntr=0.3,0.1

Type RM Length L Ch R = 1 ,7766.012,1493.576500,1493.576500,1493.576500
XS GIS Cut Line= 6
 800704.23532262810272.326774305801225.656290461809688.878611794
801671.312468734809313.594071077802531.105916861808479.262313508
 802977.89116104808107.473690923803928.682605601807392.622198654
#Sta/Elev= 30
8360.701236.51168484.016266.16338621.827268.57118743.579223.09798860.025192.2859
8982.024171.60969056.934147.1033 9134.81139.92819651.891138.29979866.494143.6191
 9900.48138.81889970.419142.24749997.152135.873510068.78137.578510096.93148.0709
10364.69140.526310795.51 147.81211062.38132.480111270.73132.480111351.07149.1218
11412.26182.0498   11438184.629411463.73198.221111502.33205.147611565.68204.4593
11654.28239.759611885.67229.573712285.95244.218812353.13233.367712695.67241.1533
#Mann= 3 , 0 , 0
8360.701  0.0401       08360.701  0.0401       012695.67  0.0401       0
#XS Ineff= 2 , 0
       0                10259.03       0
Bank Sta=8360.701,12695.67
Exp/Cntr=0.3,0.1

Type RM Length L Ch R = 1 ,6272.435,497.858800,497.858800,497.858800
XS GIS Cut Line= 6
800963.924920281810349.053246342801861.756624068810040.205030919
803028.735157492810218.918839063804245.091060793810050.967700551
805839.741630484809542.176714821807997.279045175808640.028029262
#Sta/Elev= 30
9183.857217.95639325.545206.06279502.458215.84159640.277178.86319671.526160.6701
 9754.22139.383610001.77132.954910214.19143.172510512.89142.082210616.46132.4801
10760.05132.4834 10800.7143.2112 10932.2 156.96711393.07156.841311643.47167.8982
12250.05164.7269 12301.1165.569512321.55171.785512650.13173.094613431.95164.4956
13950.19169.349614448.84163.352815194.95169.801815303.32175.572715531.02171.1857
15933.84175.912116032.17170.343916119.57179.757716371.21178.3972 16571.2192.5503
#Mann= 3 , 0 , 0
9183.857   0.044       09183.857   0.044       0 16571.2   0.044       0
#XS Ineff= 2 , 0
       0                10995.24       0
Bank Sta=9183.857,16571.2
Exp/Cntr=0.3,0.1

Type RM Length L Ch R = 1 ,5774.577,746.788300,746.788300,746.788300
XS GIS Cut Line= 6
798744.331025674812277.267122567800200.189655504 811231.38378568
801221.410370631 810720.99651912802005.071165986810509.361626565
804557.485540553810254.524818859808155.780821219808932.768737909
#Sta/Elev= 30
6418.778200.1448  7308.6158.40087567.509162.35747699.236144.58287810.806141.7865
8122.757138.13478381.956157.68529434.003173.18549571.451169.40469707.882144.3327
9966.304132.480110280.35143.239410370.74132.583910550.95132.480110690.97153.2465
10910.99152.9066   11001174.4075   11061163.840511201.02162.0942 11964.6162.3331
12111.61 172.86212255.44  165.23 14274.1168.775914508.41 160.224 15172.4161.2703
15495.54171.3641 15863.1165.989316199.48186.183416351.83  219.9316581.21219.5394
#Mann= 3 , 0 , 0
6418.778  0.0422       06418.778  0.0422       016581.21  0.0422       0
#XS Ineff= 2 , 0
       09160.245        10761.92       0
Bank Sta=6418.778,16581.21
Exp/Cntr=0.3,0.1

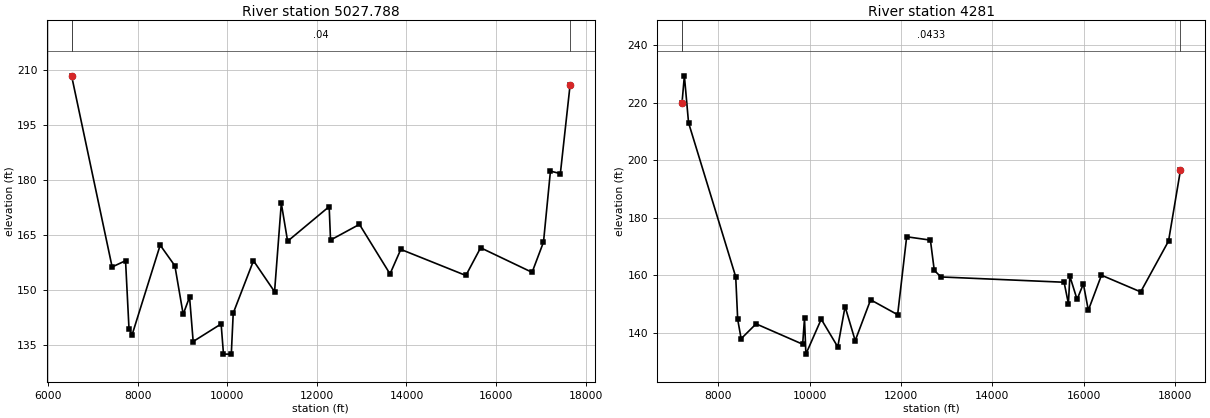
Type RM Length L Ch R = 1 ,5027.788,746.788200,746.788200,746.788200
XS GIS Cut Line= 6
798847.131787896812387.336625546800787.904687762811257.649544999
801663.559150964811151.095808864802848.431299239811399.921594366
804102.871614456811221.493455738809271.295918614 809400.13413474
#Sta/Elev= 30
6526.209208.41187431.001156.26397730.419157.96797807.384139.4157 7877.23137.7734
8503.448162.21778831.437156.57829016.782143.35569159.047148.06059239.679135.9209
9863.565 140.7159916.336132.480110090.57132.480110133.57143.659410585.49157.9662
 11056.2149.513811206.61173.636511347.41163.286412274.71172.729712305.59163.6038
12950.37167.883113632.95154.356613873.27161.059615326.12153.9372   15655161.4996
16803.92154.795817058.36163.051917213.24182.417417434.49181.731117651.65205.8974
#Mann= 3 , 0 , 0
6526.209    0.04       06526.209    0.04       017651.65    0.04       0
#XS Ineff= 2 , 0
       08871.971        10318.14       0
Bank Sta=6526.209,17651.65
Exp/Cntr=0.3,0.1

Type RM Length L Ch R = 1 ,    4281,0.000000,0.000000,0.000000
XS GIS Cut Line= 6
 799133.20298627812693.635080397800641.235597074811947.024452403
 802751.08406198811982.007814497806604.060345173810871.912353709
807579.888033062810550.268913195809358.101474166809512.981356949
#Sta/Elev= 30
7206.619 219.9097258.423229.37847350.057213.04228382.899159.39398426.181 144.561
8501.764137.84728828.986143.01679848.588135.93239889.081144.96419919.569132.4801
10255.47144.644910617.52134.9973 10777.6149.030810999.19137.168311336.72151.3977
11928.41 146.20412126.45173.340712646.12172.176312730.88161.642112876.69159.3515
15573.45157.508715668.19150.062915699.78159.6134 15858.1151.513315995.32156.9451
16104.45147.7554 16391.8159.960617250.58154.152717860.44171.836718122.45196.6108
#Mann= 3 , 0 , 0
7206.619  0.0433       07206.619  0.0433       018122.45  0.0433       0
#XS Ineff= 2 , 0
       08859.701         10313.6       0
Bank Sta=7206.619,18122.45
Exp/Cntr=0.3,0.1